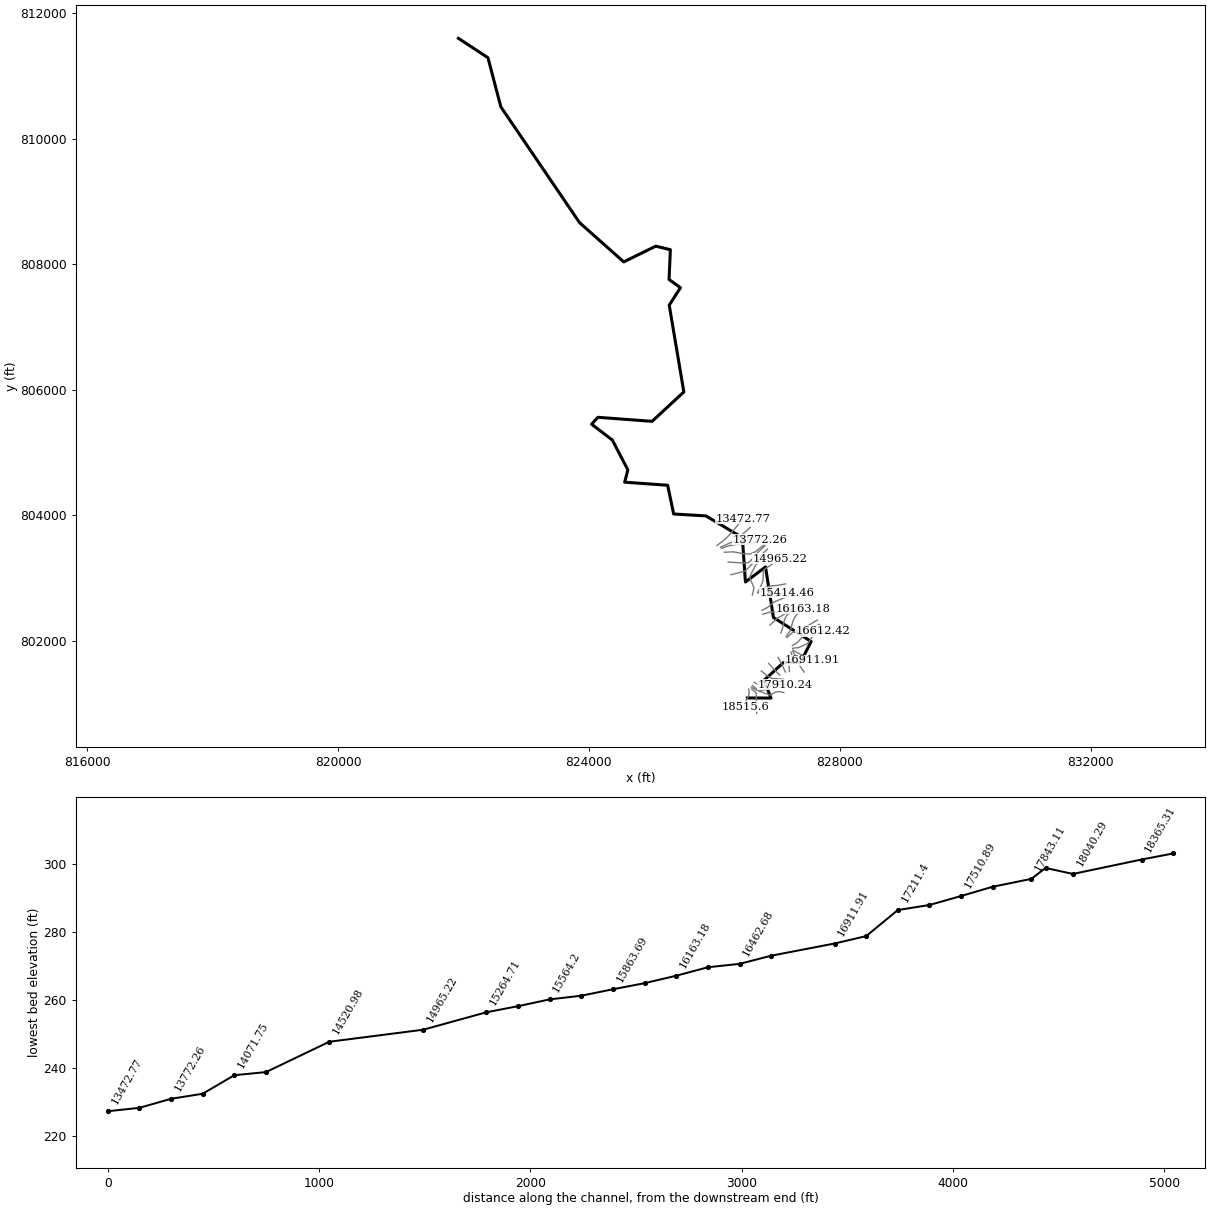
--- 18089_ras.prj (project) ---

Proj Title=18089
Current Plan=p01
Default Exp/Contr=0.3,0.1
English Units
Geom File=g01
Flow File=f01
Plan File=p01
Y Axis Title=Elevation
X Axis Title(PF)=Main Channel Distance
X Axis Title(XS)=Station
BEGIN DESCRIPTION:
RFD model 18089 exported to HEC-RAS
END DESCRIPTION:

--- 18089_ras.p01 (plan) ---

Plan Title=Plan 01
Program Version=4.10
Short Identifier=Plan 01
Geom File=g01
Flow File=f01
Subcritical Flow
Calc Critical at every XS
Secant Critical Depth

--- 18089_ras.f01 (steady flow) ---

Flow Title=Flow 01
Program Version=5.01
Number of Profiles= 6
Profile Names=10yr,25yr,50yr,100yr,100plus,500yr
River Rch & RM=18089,57, 18515.6
 1250.48 2002.89 2710.41 3349.19 4889.82 6376.91
River Rch & RM=18089,57,18365.31
 1252.51 2006.23 2715.01 3354.96 4898.24 6386.67
River Rch & RM=18089,57,18040.29
 1265.16 2026.91 2743.41 3390.47 4950.08 6446.34
River Rch & RM=18089,57,17843.11
 1266.17 2028.58 2745.71 3393.34 4954.28  6451.2
River Rch & RM=18089,57,17660.64
 1269.21 2033.58 2752.59 3401.97 4966.88 6465.77
River Rch & RM=18089,57,17510.89
 1272.25 2038.57 2759.46 3410.59 4979.46 6480.33
River Rch & RM=18089,57,17361.15
 1274.02 2041.48 2763.47 3415.62  4986.8 6488.82
River Rch & RM=18089,57, 17211.4
 1276.55 2045.64  2769.2 3422.79 4997.28 6500.94
River Rch & RM=18089,57,17061.66
 1277.56  2047.3 2771.49 3425.67 5001.47 6505.79
River Rch & RM=18089,57,16911.91
 1279.08  2049.8 2774.93 3429.97 5007.76 6513.05
River Rch & RM=18089,57,16612.42
 1315.98 2110.63 2858.87 3535.36 5161.63 6691.26
River Rch & RM=18089,57,16462.68
 1316.73 2111.87 2860.57  3537.5 5164.75 6694.85
River Rch & RM=18089,57,16312.93
    1321 2118.89 2870.24 3549.62 5182.44  6715.2
River Rch & RM=18089,57,16163.18
 1339.01 2148.97 2912.08 3602.52 5259.68 6805.86
River Rch & RM=18089,57,16013.44
  1341.7 2153.43 2918.23 3610.27 5270.99 6818.95
River Rch & RM=18089,57,15863.69
 1343.17 2155.86  2921.6 3614.49 5277.16 6826.08
River Rch & RM=18089,57,15713.95
 1346.32 2161.08 2928.83 3623.61 5290.46 6841.52
River Rch & RM=18089,57, 15564.2
 1347.52 2163.08  2931.6  3627.1 5295.56 6847.46
River Rch & RM=18089,57,15414.46
 1349.68 2166.67 2936.58 3633.38 5304.73 6858.14
River Rch & RM=18089,57,15264.71
 1356.63 2178.22 2952.61  3653.6 5334.25  6892.5
River Rch & RM=18089,57,14965.22
 1357.11 2179.02 2953.71 3654.99 5336.29 6894.87
River Rch & RM=18089,57,14520.98
 1388.85 2231.58 3026.45 3746.55 5469.96 7049.27
River Rch & RM=18089,57,14221.49
 1392.45 2237.56 3034.73 3756.98 5485.19 7066.86
River Rch & RM=18089,57,14071.75
 1395.08 2241.93 3040.79 3764.62 5496.35 7079.76
River Rch & RM=18089,57,   13922
 1396.99  2245.1 3045.18 3770.16 5504.44 7089.13
River Rch & RM=18089,57,13772.26
 1401.95 2253.37 3056.66 3784.66 5525.61  7113.7
River Rch & RM=18089,57,13622.51
 1410.52 2267.72 3076.67    3810  5562.6 7156.91
River Rch & RM=18089,57,13472.77
 1414.17 2273.86 3085.25 3820.89 5578.49 7175.57
River Rch & RM=18089,57,13173.28
 1420.83 2285.05 3100.85 3840.66 5607.37 7209.33
River Rch & RM=18089,57,13023.53
  1445.9  2326.4 3157.93 3912.36 5712.04 7328.75
River Rch & RM=18089,57,12873.78
 1448.27 2330.33 3163.38 3919.23 5722.07 7340.31
River Rch & RM=18089,57,12724.04
 1454.46 2340.59  3177.6 3937.14 5748.23 7370.31
River Rch & RM=18089,57,12424.55
 1459.62 2349.19 3189.54 3952.21 5770.23 7395.67
River Rch & RM=18089,57,12125.06
 1468.44 2363.81 3209.77 3977.69 5807.43 7438.23
River Rch & RM=18089,57,11825.57
 1473.58 2372.37 3221.66 3992.71 5829.36 7463.49
River Rch & RM=18089,57,11376.33
 1481.76 2385.99 3240.57 4016.59 5864.22 7503.61
River Rch & RM=18089,57,11076.84
 1534.12 2471.97 3358.94 4164.87 6080.71 7747.12
River Rch & RM=18089,57,10777.35
 1535.05 2473.52 3361.09 4167.59 6084.68 7751.64
River Rch & RM=18089,57,10477.86
  1671.4 2696.19 3666.56 4549.05 6641.61 8367.38
River Rch & RM=18089,57,9729.131
  1746.4 2820.03 3837.67 4764.08 6955.56 8716.71
River Rch & RM=18089,57, 9130.15
 1756.21 2836.53 3860.73 4793.34 6998.28 8765.24
River Rch & RM=18089,57,8830.659
 1759.45 2841.99 3868.37 4803.06 7012.46 8781.39
River Rch & RM=18089,57,8231.677
  1774.4 2867.17 3903.57 4847.77 7077.74 8855.55
River Rch & RM=18089,57,7737.828
 1792.61  2897.9 3946.62 4902.52 7157.68 8946.56
River Rch & RM=18089,57,7479.109
 1944.27 3154.95  4307.6  5362.7 7829.54 9709.83
River Rch & RM=18089,57,6830.456
 1962.94 3186.76 4352.42 5420.01 7913.21 9804.85
River Rch & RM=18089,57,6591.021
 1973.81 3205.31 4378.59  5453.5 7962.11 9860.45
River Rch & RM=18089,57,6416.761
  1974.6 3206.67 4380.51 5455.97 7965.71 9864.57
River Rch & RM=18089,57,6043.454
 1979.96 3215.86  4393.5 5472.62 7990.03 9892.32
River Rch & RM=18089,57,5701.538
 1983.14  3221.3 4401.19 5482.48 8004.43 9908.75
River Rch & RM=18089,57,5162.227
 1987.63 3229.03 4412.16 5496.58    8025 9932.35
Boundary for River Rch & Prof#=18089,57,1
Up Type= 0
Dn Type= 2
Boundary for River Rch & Prof#=18089,57,2
Up Type= 0
Dn Type= 2
Boundary for River Rch & Prof#=18089,57,2
Up Type= 0
Dn Type= 2
Boundary for River Rch & Prof#=18089,57,2
Up Type= 0
Dn Type= 2
Boundary for River Rch & Prof#=18089,57,2
Up Type= 0
Dn Type= 2
Boundary for River Rch & Prof#=18089,57,2
Up Type= 0
Dn Type= 2

--- 18089_ras.g01 (geometry) ---

Geom Title=18089
Program Version=4.10

River Reach=18089,57
Reach XY= 30
826526.164274186801086.783345419826903.277653489801084.248059013
826791.947847694 801367.47240138827099.625358436801648.776861623
827373.658904913801653.664308006827542.918829471801986.534071762
826941.989297065802369.393476327 826815.27866328803175.031434258
 826495.56239465802934.940479283826446.468592884803643.136689337
825866.960989477 803988.75471235825351.104137064804019.415741454
825255.716073069804477.315033519824570.146235855804526.430837535
824621.187206954804722.645405478824373.668564292805197.957055866
824043.110311688805451.255450242824143.963769796 805561.00279269
825007.218979332805496.418636937825513.729396017 805965.16863692
825280.593100429807348.195162396825459.126206904807627.148483834
825277.900235745807758.224101592825298.860374987808233.527144519
825065.812729299808289.387386943824555.200221508808038.273612445
823850.248005391 808665.05231703822596.230296049810510.264940905
822390.501129361811294.119107565821919.146962734811602.712857571

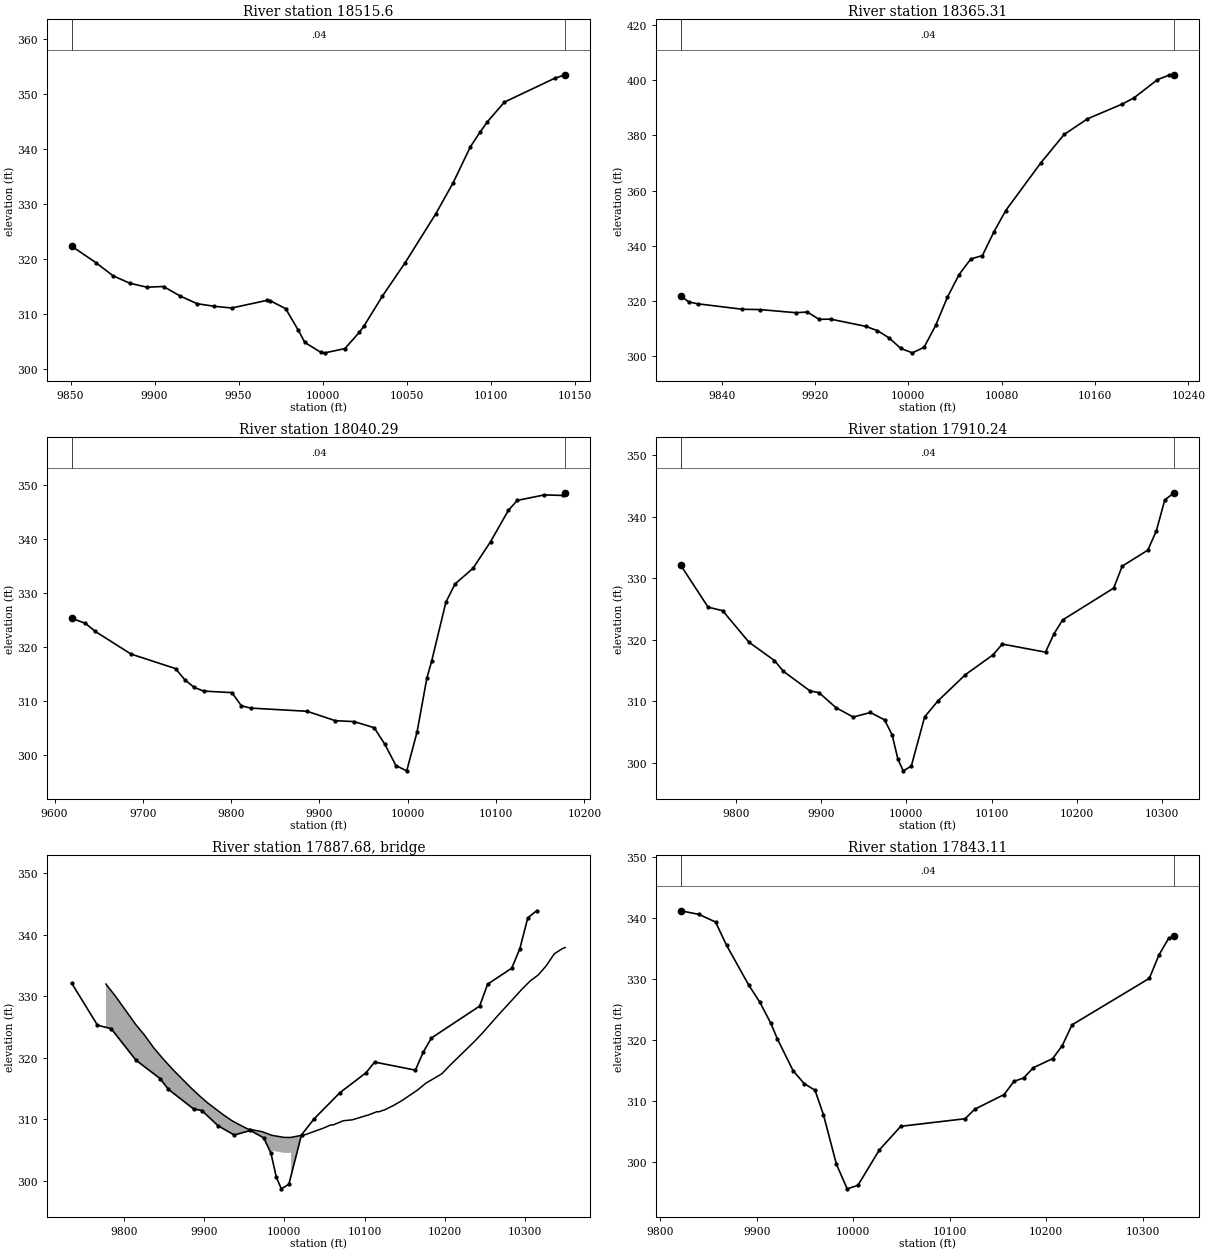
Type RM Length L Ch R = 1 , 18515.6,150.296600,150.296600,150.296600
XS GIS Cut Line= 6
826548.207449343801229.003464182826555.523705031801176.822932755
826553.615675097801153.151392033 826542.54462685801113.428462268
 826502.91802632801037.345074147826488.329753076800949.025134141
#Sta/Elev= 30
 9850.65322.39249865.046319.41069875.243317.02469885.272315.6613  9895.3314.9522
9905.329315.06659915.362313.31459925.394311.94139935.591311.47459945.826 311.167
9966.901312.55329968.569312.52349978.007311.03929985.336307.2135 9989.42304.9041
    9999303.099410001.45303.021810013.24303.796610021.78306.734510024.75307.9711
10035.56313.332910049.16319.423310067.34328.290110077.62333.896810087.91340.4513
10093.63343.091610098.09345.015410108.15348.560610138.33 352.92710144.34353.5255
#Mann= 3 , 0 , 0
 9850.65    0.04       0 9850.65    0.04       010144.34    0.04       0
#XS Ineff= 2 , 0
       09956.691                       0
Bank Sta=9850.65,10144.34
Exp/Cntr=0.3,0.1

Type RM Length L Ch R = 1 ,18365.31,325.011400,325.011400,325.011400
XS GIS Cut Line= 3
826593.875104368801229.484130979826668.084748834801165.663836673
826675.505713373800840.625593677
#Sta/Elev= 30
9804.946 321.8399811.823319.67469819.619318.97999857.832317.00969873.169316.8876
9903.488315.7712 9913.49 316.0089923.493313.37599933.496313.43389963.503310.8283
9973.506309.28619983.509306.66879993.511 302.84410003.51301.232710013.52303.2293
10023.52311.205610033.52321.356410043.52329.562910053.53335.182310063.53336.4711
10073.53345.143810083.53352.763810113.54369.988610133.55380.286210153.55 385.957
10183.56391.330810193.56 393.59110213.57400.143210223.57401.776110227.95401.9067
#Mann= 3 , 0 , 0
9804.946    0.04       09804.946    0.04       010227.95    0.04       0
#XS Ineff= 2 , 0
       09954.479                       0
Bank Sta=9804.946,10227.95
Exp/Cntr=0.3,0.1

Type RM Length L Ch R = 1 ,18040.29,130.058400,130.058400,130.058400
XS GIS Cut Line= 6
826591.439839145801257.366014409826688.331385911801204.140550926
826889.038634807801130.955277121826980.107376909801182.014121861
827038.979432987801187.350441906 827107.69705572801172.621259142
#Sta/Elev= 30
9619.323 325.3229634.794324.39299646.203322.87339686.546318.68179736.969315.9832
9747.613313.87139758.257312.47839768.901311.80319800.833311.52349811.477309.0853
9822.121308.64889885.986308.05489917.918 306.3059939.206306.14169961.953305.0038
9974.159301.89229986.581297.96789998.798296.995710010.46304.172710021.74314.3174
10026.96317.314410043.14328.299710053.52331.705410073.85334.599210093.86339.5765
10113.92345.368810124.01347.215410154.66348.2388 10175.5348.138110178.31348.6315
#Mann= 3 , 0 , 0
9619.323    0.04       09619.323    0.04       010178.31    0.04       0
#XS Ineff= 2 , 0
       09927.373                       0
Bank Sta=9619.323,10178.31
Exp/Cntr=0.3,0.1

Type RM Length L Ch R = 1 ,17910.24,67.122000,67.122000,67.122000
XS GIS Cut Line= 6
826606.655875593801285.151869193826680.514433026801225.755127206
826739.911175013801207.161364511826806.538824707801215.425259054
826943.926071405801299.097191229827136.061619371801300.130178049
#Sta/Elev= 30
9735.228332.12079767.385325.30249784.434324.73559815.255319.62679845.186316.6514
9855.665314.9029  9887.1311.69969897.374311.44839917.528308.98159937.681  307.48
9957.834308.21359974.397307.01879983.354304.55169990.075300.63659996.338298.7468
10005.75299.505110021.43307.502410037.11310.100710069.34314.364510101.72 317.572
10112.51319.315210163.22318.007110173.22  320.9810183.22323.224310243.22328.3985
10253.22331.961410283.22334.551510293.22337.677510303.22342.732110314.28343.8672
#Mann= 3 , 0 , 0
9735.228    0.04       09735.228    0.04       010314.28    0.04       0
#XS Ineff= 2 , 0
       09967.269                       0
Bank Sta=9735.228,10314.28
Exp/Cntr=0.3,0.1

Type RM Length L Ch R = 3 ,17887.68,,,
BEGIN DESCRIPTION:
END DESCRIPTION:
Bridge Culvert--1,0,-1,-1, 0
Deck Dist Width WeirC Skew NumUp NumDn MinLoCord MaxHiCord MaxSubmerge Is_Ogee
23.061000,21.000000,2.6,0, 47, 45, , , 0.95, 0, 0,0,,
 9777.91 9789.63 9814.99 9825.58 9837.56 9849.54 9861.52 9883.65 9893.92 9904.18
 9924.47 9934.54 9944.61 9954.64 9972.45 9984.44 9984.44 9999.3810007.0410008.44
10008.4410026.5210048.3310057.8810061.3210073.5610084.5610105.0510115.3010117.78
10125.5510135.8010146.0410166.1110176.1210196.1310206.1310236.1510246.1510266.16
10296.1810306.1810316.1910326.1910336.2010346.2010349.82
  331.98  330.03  325.42  323.75  321.60  319.77  318.06  315.15  313.90  312.73
  310.73  309.83  309.11  308.46  308.02  307.43  307.43  307.10  307.08  307.10
  307.10  307.56  308.58  309.11  309.14  309.80  309.94  310.75  311.26  311.25
  311.60  312.26  313.03  314.80  315.88  317.41  318.77  322.58  323.94  326.90
  331.17  332.48  333.45  334.94  336.88  337.72  337.91
 -668.02 -669.97 -674.58 -676.25 -678.40 -680.23 -681.94 -684.85 -686.10 -687.27
 -689.27 -690.17 -690.89 -691.54 -691.98 -692.57  304.93  304.60  304.58  304.60
 -692.90 -692.44 -691.42 -690.89 -690.86 -690.20 -690.06 -689.25 -688.74 -688.75
 -688.40 -687.74 -686.97 -685.20 -684.12 -682.59 -681.23 -677.42 -676.06 -673.10
 -668.83 -667.52 -666.55 -665.06 -663.12 -662.28 -662.09
 9777.91 9789.63 9814.99 9825.58 9837.56 9849.54 9861.52 9883.65 9904.18 9924.47
 9934.54 9954.64 9972.45 9985.92 9995.64 9995.6410007.0410019.6410019.6410026.52
10035.3510057.8810061.3210073.5610084.5610105.0510115.3010117.7810125.5510135.80
10146.0410166.1110176.1210196.1310206.1310236.1510246.1510266.1610296.1810306.18
10316.1910326.1910336.2010346.2010349.82
  331.98  330.03  325.42  323.75  321.60  319.77  318.06  315.15  312.73  310.73
  309.83  308.46  308.02  307.36  307.18  307.18  307.08  307.36  307.36  307.56
  307.95  309.11  309.14  309.80  309.94  310.75  311.26  311.25  311.60  312.26
  313.03  314.80  315.88  317.41  318.77  322.58  323.94  326.90  331.17  332.48
  333.45  334.94  336.88  337.72  337.91
 -668.02 -669.97 -674.58 -676.25 -678.40 -680.23 -681.94 -684.85 -687.27 -689.27
 -690.17 -691.54 -691.98 -692.64 -692.82  304.68  304.58  304.86 -692.64 -692.44
 -692.05 -690.89 -690.86 -690.20 -690.06 -689.25 -688.74 -688.75 -688.40 -687.74
 -686.97 -685.20 -684.12 -682.59 -681.23 -677.42 -676.06 -673.10 -668.83 -667.52
 -666.55 -665.06 -663.12 -662.28 -662.09
BR Coef=-1 , 0 , 0 ,, 0 ,,,0.8,0,1,0,
WSPro=,,,, 1 ,,,, 0 ,,,, 0 ,,,,-1 ,-1 ,-1 , 0 , 0 , 0 , 0 , 0
BC Design=,, 0 ,, 0 ,,,,,,

Type RM Length L Ch R = 1 ,17843.11,182.474800,182.474800,182.474800
XS GIS Cut Line= 6
826633.513532877801334.218743011 826749.72454977801268.624080122
826840.110896289801312.526019841826870.584007382801332.152769372
826951.168565333801345.511706784827110.753442317801357.460946396
#Sta/Elev= 30
9821.042341.22939839.797340.64519857.198339.38489868.681335.53629891.647329.0113
 9903.13326.19929914.613322.72019921.172 320.2219937.579314.95779949.062312.8459
9960.352311.73619969.081307.72519982.587299.56999993.704295.540310004.82296.1114
10027.06301.928510049.29305.817710115.97307.0586 10126.1308.632410156.51311.0366
10166.65 313.19510176.74313.762510186.77315.441210206.83316.941810216.86319.0902
10226.88322.483110307.11330.133310317.14334.000510327.16336.711410332.93 337.031
#Mann= 3 , 0 , 0
9821.042    0.04       09821.042    0.04       010332.93    0.04       0
#XS Ineff= 2 , 0
       0                               0
Bank Sta=9821.042,10332.93
Exp/Cntr=0.3,0.1

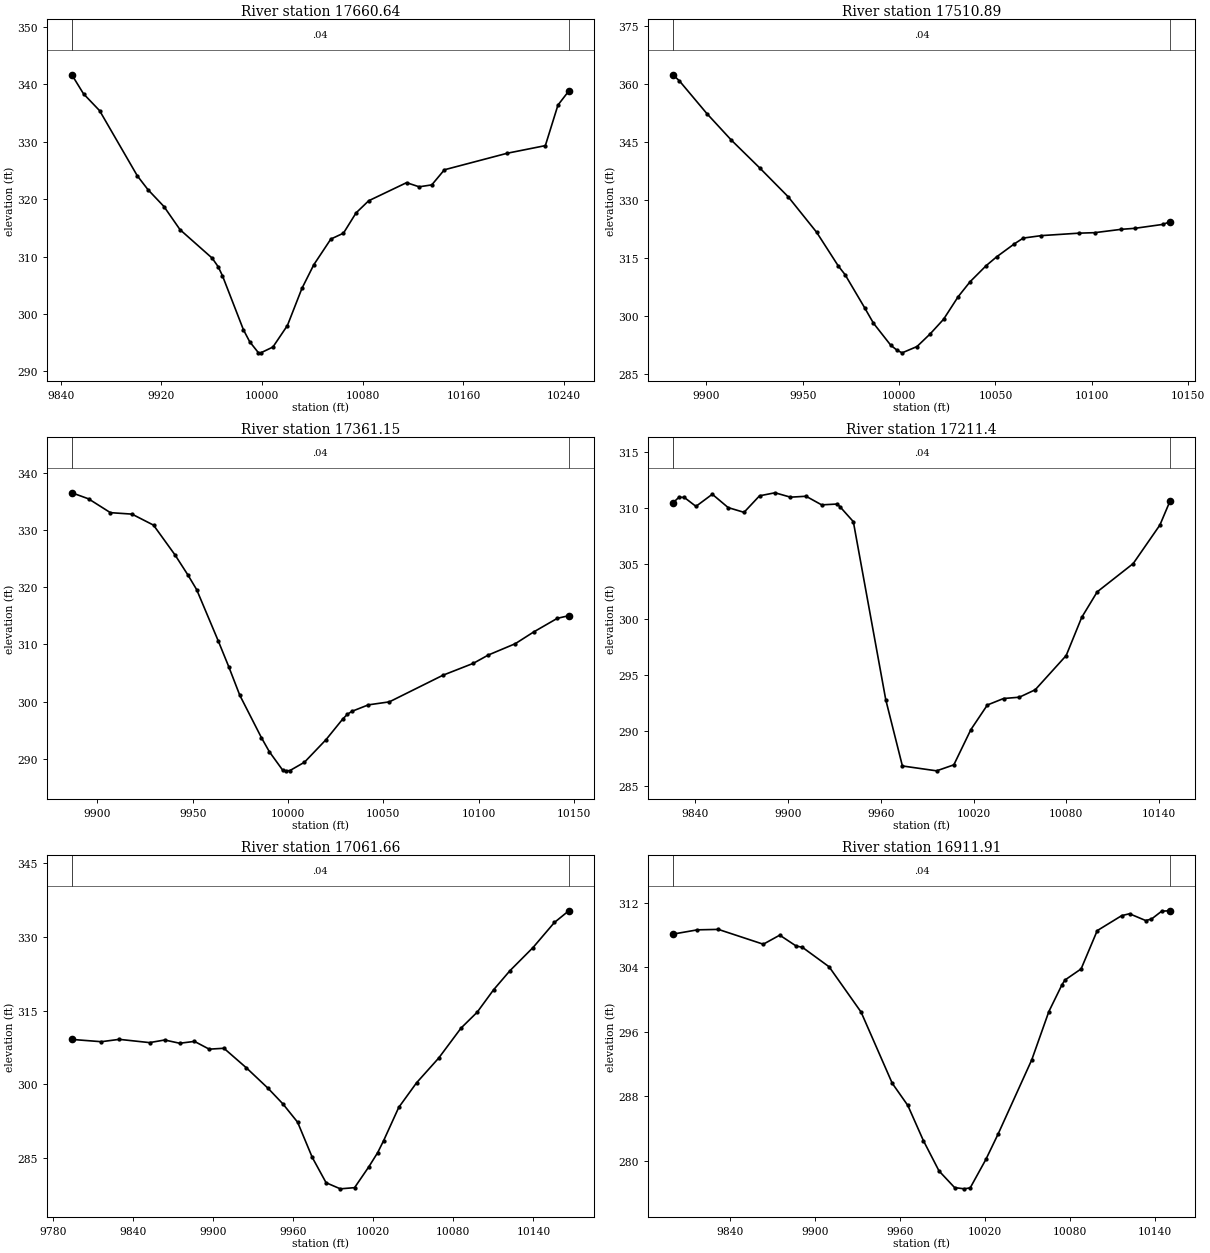
Type RM Length L Ch R = 1 ,17660.64,149.745400,149.745400,149.745400
XS GIS Cut Line= 6
826747.714081049801517.394699067 826841.39129135801442.861233354
 826859.06129846801430.414633736826868.364980191801424.892424554
  826914.6750741801398.429951891827103.609163702801384.696106508
#Sta/Elev= 30
9848.856341.66639858.167338.34689870.946335.41189900.886 324.0719909.283321.6789
9922.062318.72189934.841  314.699960.399309.72859965.132308.24449968.567306.6595
9985.213297.2598 9990.18295.1786 9997.07293.2725    9999293.241210008.64294.2526
10020.16298.001410031.68 304.45810041.09308.570110054.66313.056610064.69314.0806
10074.72317.615110084.74 319.72510114.82322.876810124.85322.157810134.87322.4904
 10144.9325.120810195.03328.012410225.11329.328510235.14336.393110243.77338.8442
#Mann= 3 , 0 , 0
9848.856    0.04       09848.856    0.04       010243.77    0.04       0
#XS Ineff= 2 , 0
       0                               0
Bank Sta=9848.856,10243.77
Exp/Cntr=0.3,0.1

Type RM Length L Ch R = 1 ,17510.89,149.745300,149.745300,149.745300
XS GIS Cut Line= 6
 826863.78363133801637.362037044826879.245539118801622.079872003
826943.342767162801552.558720751826944.604692022801551.007093977
826989.501674641801503.651604827827043.276427975801452.371708675
#Sta/Elev= 30
  9882.7362.3973 9886.06360.79379900.286352.35369912.929345.52229927.682338.3152
9942.434330.87139957.187321.70389968.476312.9516 9971.94310.74919982.078302.2032
9986.692298.18599995.679292.4755    9999291.164310001.57290.516410009.28292.1443
10016.11295.408610023.06299.185310030.64305.028510036.84308.902310045.18313.0588
10050.62315.338810059.71318.6575 10064.4320.182310073.85320.821110093.28321.4526
10101.49321.581710115.31322.448910122.26322.701510136.75323.713110140.56324.3996
#Mann= 3 , 0 , 0
  9882.7    0.04       0  9882.7    0.04       010140.56    0.04       0
#XS Ineff= 2 , 0
       0                               0
Bank Sta=9882.7,10140.56
Exp/Cntr=0.3,0.1

Type RM Length L Ch R = 1 ,17361.15,149.745400,149.745400,149.745400
XS GIS Cut Line= 6
827015.937510041801732.603396252827024.360236356801717.946124242
827070.047058922801631.762076265827082.920611989801607.258394779
827129.749803087801505.920905733827133.011436849801499.639350025
#Sta/Elev= 30
 9886.55336.5169 9895.32335.4584 9906.79333.04039918.107332.78419929.425330.8572
9940.742325.62979947.532322.1089 9952.06319.57969963.377310.62069968.887306.1119
9974.695301.10289986.012293.70779990.242291.2082 9997.33287.9469    9999 287.879
   10001287.925210008.64289.383910019.93293.321710028.68296.921310031.17 297.775
10033.64298.300910042.18299.4197 10053.2299.944610081.31304.600510097.26306.6837
10105.15308.1401 10119.3310.120510128.99312.180610141.35 314.55710147.39315.0184
#Mann= 3 , 0 , 0
 9886.55    0.04       0 9886.55    0.04       010147.39    0.04       0
#XS Ineff= 2 , 0
       0                               0
Bank Sta=9886.55,10147.39
Exp/Cntr=0.3,0.1

Type RM Length L Ch R = 1 , 17211.4,149.745400,149.745400,149.745400
XS GIS Cut Line= 6
827221.988049393801818.528269802827236.109365603801774.558230342
827237.595656327801743.005754254827223.077370261801679.854798464
827190.537757366801594.568421293827197.492556879801508.636715617
#Sta/Elev= 30
9825.544310.46769829.413310.9736 9832.88310.9466 9840.38310.14829850.957311.2379
9861.223310.03849871.488 309.612 9881.51311.09599891.521311.36899901.533310.9748
9911.607311.05639921.698 310.2849931.789310.35749933.786310.08189942.197308.7748
 9963.17292.78439973.937286.83229996.067286.393910007.21286.932510018.22290.0925
 10028.9292.307910039.37292.889710049.61293.007710059.85293.6736 10079.9296.7497
10089.93300.173810099.97302.471610123.25  305.0110140.53308.472910147.07310.6261
#Mann= 3 , 0 , 0
9825.544    0.04       09825.544    0.04       010147.07    0.04       0
#XS Ineff= 2 , 0
       0                               0
Bank Sta=9825.544,10147.07
Exp/Cntr=0.3,0.1

Type RM Length L Ch R = 1 ,17061.66,149.745400,149.745400,149.745400
XS GIS Cut Line= 6
827252.467543936801824.255406886827272.638481782801795.005111364
827292.458879427801757.876994423827352.345989253801618.887105713
827366.178240567801593.296213993827431.736077762801500.100108008
#Sta/Elev= 30
9794.231309.12839816.307308.66329829.762309.14069852.439308.47899863.775309.0097
9875.026308.34719886.068308.7264 9897.11307.14889908.152307.32619925.007303.3412
9941.277299.16889952.319296.01549963.322292.30029974.331285.1252 9984.66279.9856
9995.329278.743510005.99278.983710016.74283.254910023.31286.114810027.73288.5312
10039.09295.3094 10052.4300.302710069.05305.352910085.76311.443310097.82 314.662
10110.08319.210910122.35323.098510139.63327.807810155.66332.908810166.46335.2866
#Mann= 3 , 0 , 0
9794.231    0.04       09794.231    0.04       010166.46    0.04       0
#XS Ineff= 2 , 0
       0                               0
Bank Sta=9794.231,10166.46
Exp/Cntr=0.3,0.1

Type RM Length L Ch R = 1 ,16911.91,299.490800,299.490800,299.490800
XS GIS Cut Line= 6
827250.156221023801851.188505436827353.549970221801790.427268043
827425.376039927801757.646845644827427.213766239801756.857692933
 827476.77404194801733.879492513827560.103249559 801688.78438464
#Sta/Elev= 30
9800.121308.10179817.339308.62919832.073308.68369863.734306.84919875.333307.9699
9886.932 306.6239891.285306.4687 9910.13304.05269932.633298.45679954.618289.6352
 9965.61286.88749976.602282.52439987.594278.78119998.587276.720310005.42276.5673
10009.58 276.693 10020.6280.206510029.19283.339510052.96292.544210064.98 298.508
10074.28301.845210076.35302.417510087.72303.791310099.09308.531510116.31310.3855
10121.83310.6199 10133.2309.782910137.32309.962110144.57310.945910150.38 310.988
#Mann= 3 , 0 , 0
9800.121    0.04       09800.121    0.04       010150.38    0.04       0
#XS Ineff= 2 , 0
       0                               0
Bank Sta=9800.121,10150.38
Exp/Cntr=0.3,0.1

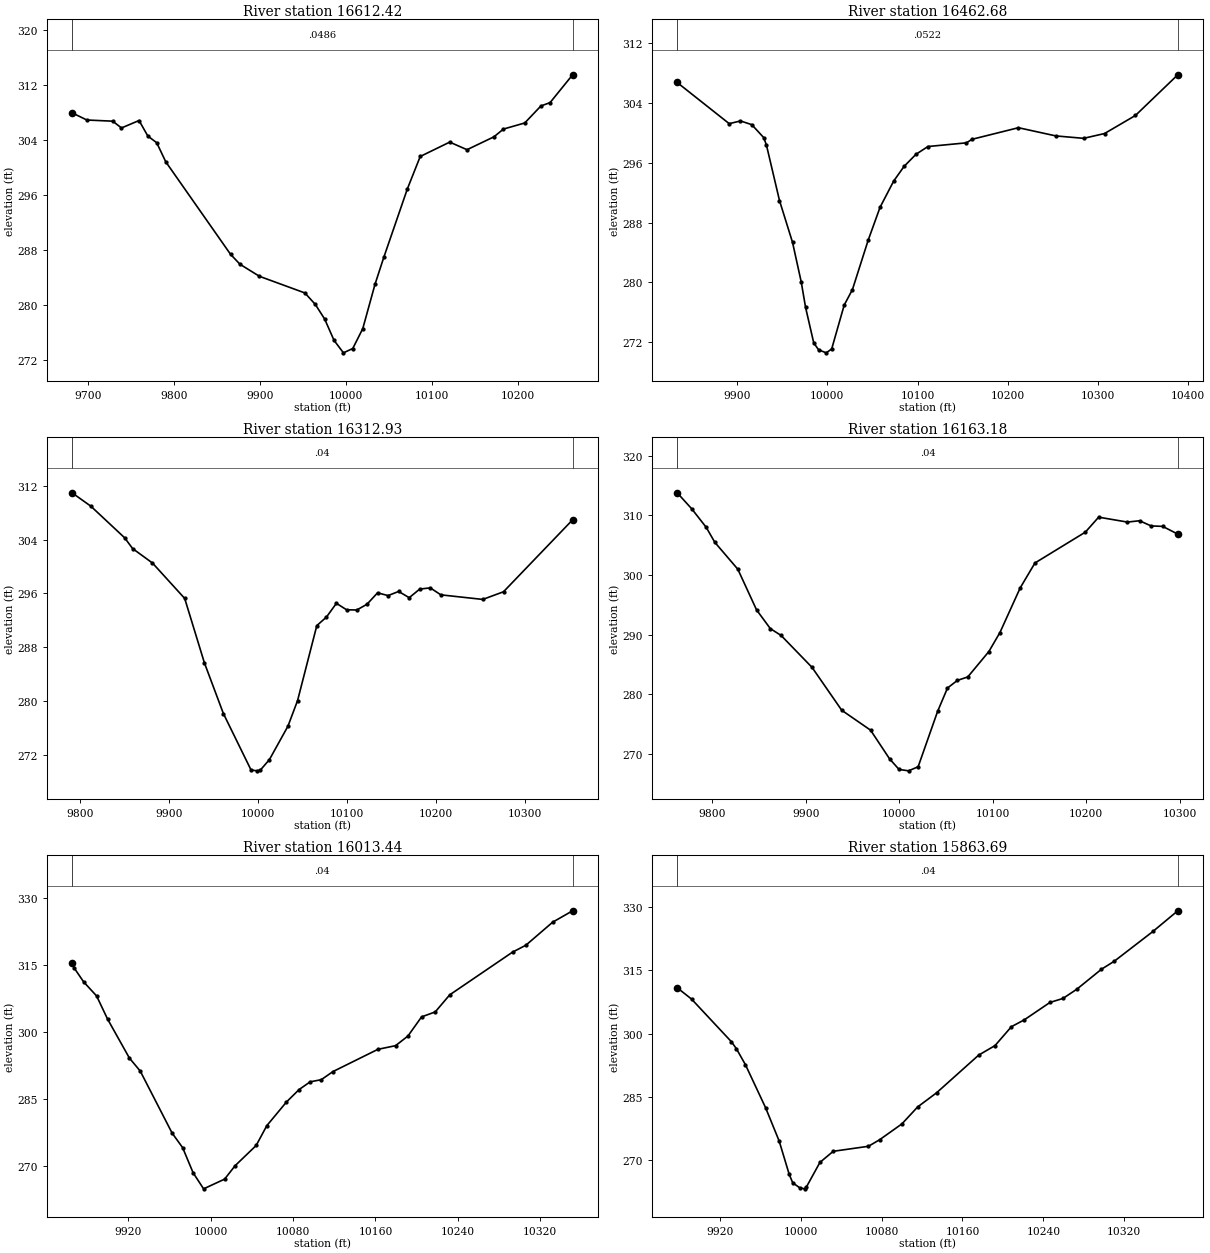
Type RM Length L Ch R = 1 ,16612.42,149.745300,149.745300,149.745300
XS GIS Cut Line= 6
827247.773262614801878.956349327827342.441880004801889.494806269
827484.934484752801952.679175303827571.462162945802074.388837717
827637.979116433802116.696374395827729.446008436802154.942530168
#Sta/Elev= 30
9681.781307.90849699.022 306.8589729.107306.68689739.273305.7007  9759.7306.7836
9769.914304.52449780.213303.55489790.759300.77499865.989287.33389876.962285.8801
 9899.57 284.1289952.465281.70369964.541280.0374 9975.44 277.905 9986.34274.8033
9997.239272.994410008.08273.6241 10019.7276.509710033.91282.953610044.15286.8841
10071.55296.8418 10086.5301.555510120.76303.642310140.88 302.53810172.15304.4125
10183.17305.538110207.97306.427810226.72308.896510237.43309.390910263.61313.4362
#Mann= 3 , 0 , 0
9681.781  0.0486       09681.781  0.0486       010263.61  0.0486       0
#XS Ineff= 2 , 0
       0                               0
Bank Sta=9681.781,10263.61
Exp/Cntr=0.3,0.1

Type RM Length L Ch R = 1 ,16462.68,149.745400,149.745400,149.745400
XS GIS Cut Line= 6
827244.026761771801922.613111992 827319.43939338801967.605103181
827455.241367463802111.130212368827510.891960784802160.731739381
827574.152592293802205.066488311827677.190335439802260.211204735
#Sta/Elev= 30
9833.541306.71479891.202301.21429903.723301.57629916.243301.07849929.503299.3415
 9932.49298.34339946.944290.94019961.397285.34979971.052 280.0539975.851276.6605
9984.902271.91659990.305270.99069998.751270.589810004.79271.108910018.67276.9738
10027.82279.052110045.18285.617610058.44290.049310073.52293.543310084.95295.4922
10098.21297.116410111.46298.157610154.16298.650910160.37 299.12410211.76300.6719
10253.27299.574810284.03299.252310307.23299.893710341.48302.310210388.41 307.745
#Mann= 3 , 0 , 0
9833.541  0.0522       09833.541  0.0522       010388.41  0.0522       0
#XS Ineff= 2 , 0
       0                               0
Bank Sta=9833.541,10388.41
Exp/Cntr=0.3,0.1

Type RM Length L Ch R = 1 ,16312.93,149.745400,149.745400,149.745400
XS GIS Cut Line= 6
827159.995500662802053.161841984827250.006105433 802133.75572539
827284.178404299802149.857375544827362.664784447802170.806265895
827409.019862802802189.958947457827643.037166901802329.012515254
#Sta/Elev= 30
9791.093310.98239812.321308.97979850.235304.2818 9859.21302.67869881.537300.5288
9917.744295.25719939.853285.68689961.209278.13169992.287269.7312    9999 269.601
 10002.6269.684110012.95271.271410033.77276.241310044.59280.054610066.23291.2142
10077.05292.483910088.25294.5312 10099.7 293.56810111.16 293.53910122.64294.3942
10134.49 296.09210146.35295.6825 10158.2296.298110170.06295.369610181.91296.6504
10193.77296.830310205.62295.792310252.75295.110810276.05296.251510353.73306.9594
#Mann= 3 , 0 , 0
9791.093    0.04       09791.093    0.04       010353.73    0.04       0
#XS Ineff= 2 , 0
       0                               0
Bank Sta=9791.093,10353.73
Exp/Cntr=0.3,0.1

Type RM Length L Ch R = 1 ,16163.18,149.745400,149.745400,149.745400
XS GIS Cut Line= 6
827146.002081767802062.985036705827213.057165813  802163.6456148
827251.152046826802304.875357736827273.492875482802359.648430609
827319.677648129802423.357914474827418.136979686802507.424215559
#Sta/Elev= 30
9762.224313.79589777.834311.09589793.317307.99079802.485305.48359827.136300.9619
9847.199294.13139861.912290.99589873.448289.84169906.597284.47829938.363277.2805
9969.213273.94239989.529269.13449999.682267.3501 10009.9267.112910020.14267.8011
10040.97277.092410051.56281.018310062.15282.297110073.25282.874610095.85287.1423
10107.71290.336310129.41297.837110145.18302.010610199.12307.187510213.34309.7019
10244.11 308.87710257.13309.100210269.48308.231410281.84308.156210298.06306.8574
#Mann= 3 , 0 , 0
9762.224    0.04       09762.224    0.04       010298.06    0.04       0
#XS Ineff= 2 , 0
       0                               0
Bank Sta=9762.224,10298.06
Exp/Cntr=0.3,0.1

Type RM Length L Ch R = 1 ,16013.44,149.745400,149.745400,149.745400
XS GIS Cut Line= 6
827059.986926479802123.366536438827082.899126263802181.275476135
827116.757330479802329.406439482827141.432221397802382.713493469
827192.012501461802447.057266365827290.195434361802532.999662341
#Sta/Elev= 30
 9865.53315.5561 9867.35314.44699876.885311.21749889.394308.09139900.008302.9273
9921.234294.18889931.734291.28579962.657277.41119972.909274.13659983.077268.5109
9993.245264.929110013.62267.101110023.83270.109910044.25274.631310054.55279.0534
 10073.6284.347610085.95287.155210096.67288.873310107.46289.354510118.77291.1681
10162.43296.148510179.54296.965310191.53299.118510204.77303.404510218.02304.5161
 10232.1 308.33910293.05317.894510306.03319.447210331.98324.594810351.36327.1482
#Mann= 3 , 0 , 0
 9865.53    0.04       0 9865.53    0.04       010351.36    0.04       0
#XS Ineff= 2 , 0
       0                               0
Bank Sta=9865.53,10351.36
Exp/Cntr=0.3,0.1

Type RM Length L Ch R = 1 ,15863.69,149.745400,149.745400,149.745400
XS GIS Cut Line= 6
826884.162927378802246.792655002826948.564052215802304.099959475
826996.671490466802355.389849796827069.055848788802392.040679149
827107.736086985802415.711316477827275.086464012802545.809441551
#Sta/Elev= 30
9877.816 310.8949892.006308.20769931.486298.06479936.399296.4141 9945.31292.6301
 9965.27282.4096  9978.7274.50019988.685266.54859992.129 264.573    9999263.3998
10003.83263.1411 10005.4263.469610019.04269.422210032.21272.056910067.01273.2461
10078.06274.797610100.16278.5658 10115.7282.589510134.39 285.93810176.07294.8958
10192.24297.156910208.46301.643410221.19303.273110246.63 307.40710259.36308.3429
10273.11310.530810297.53315.287110310.25317.195710348.42324.250610373.05329.1691
#Mann= 3 , 0 , 0
9877.816    0.04       09877.816    0.04       010373.05    0.04       0
#XS Ineff= 2 , 0
       0                               0
Bank Sta=9877.816,10373.05
Exp/Cntr=0.3,0.1

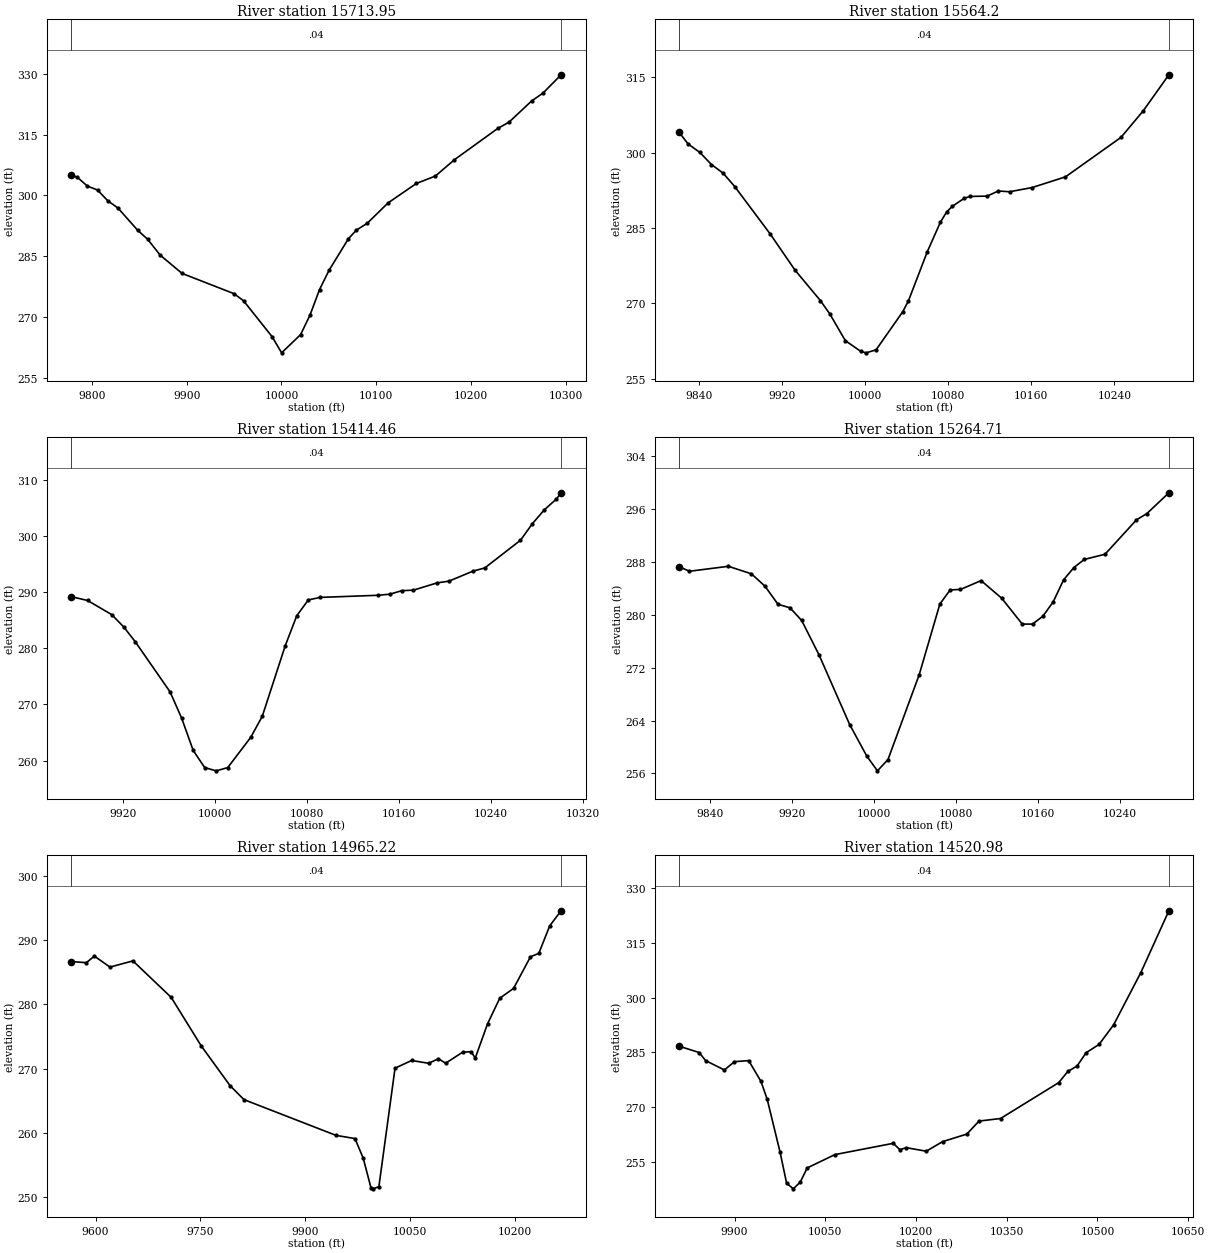
Type RM Length L Ch R = 1 ,15713.95,149.745300,149.745300,149.745300
XS GIS Cut Line= 6
826769.337752273 802420.45285481826891.864666845802457.132451087
 827029.84522135802455.476364363827063.283443868802461.231909554
 827119.09710054802483.398853261827251.090809797 802566.15358317
#Sta/Elev= 30
9778.531305.0347 9784.61304.49649795.346302.32359806.082301.33769816.818298.7032
9827.538296.92149848.377 291.4339858.797289.24049872.082285.31469895.182280.8054
9950.019275.81319960.049274.05489990.138 265.21810000.15261.244810020.16265.7267
10030.16270.577610040.16276.833610050.23281.594410070.53289.327210078.93291.4578
10090.42293.149310112.51298.189610142.28302.965210162.33304.787810182.36308.8039
10228.09316.5131   10240 318.06510263.83323.289110275.74325.200410294.91329.7346
#Mann= 3 , 0 , 0
9778.531    0.04       09778.531    0.04       010294.91    0.04       0
#XS Ineff= 2 , 0
       0                               0
Bank Sta=9778.531,10294.91
Exp/Cntr=0.3,0.1

Type RM Length L Ch R = 1 , 15564.2,149.745400,149.745400,149.745400
XS GIS Cut Line= 6
826757.357854365802482.348993995826844.866939572802528.533207799
826882.032435921802554.687289063826942.230578964802607.385637123
826971.205341755802625.625375178827168.176250415802705.200880867
#Sta/Elev= 30
9821.108303.99189829.686301.69639840.911300.03069852.135297.6064 9863.36295.9014
9874.585293.2214 9908.77283.77029932.464276.6363 9956.92270.56939965.986 267.918
9980.933262.5985 9995.88260.4522   10001 260.16710010.55 260.76710036.32 268.368
10041.74 270.52510059.86280.281610072.47286.154310078.63288.232110084.04289.3148
10095.21290.886810100.84291.267810117.44291.338810128.24292.353210139.04292.2047
10160.65293.033310192.83295.161910246.25303.013210267.62308.275710292.38315.4659
#Mann= 3 , 0 , 0
9821.108    0.04       09821.108    0.04       010292.38    0.04       0
#XS Ineff= 2 , 0
       0                               0
Bank Sta=9821.108,10292.38
Exp/Cntr=0.3,0.1

Type RM Length L Ch R = 1 ,15414.46,149.745400,149.745400,149.745400
XS GIS Cut Line= 6
826742.151600362802694.900585694826784.498590365802709.772290079
826814.067433279802714.312242199826914.024810516802711.915757779
826976.839681598 802717.73458116827158.882345778802762.920920171
#Sta/Elev= 30
 9875.09 289.1649889.114288.49329910.097285.97739920.571  283.789930.688 281.116
9960.916272.20279970.919267.53879980.926261.81789990.938258.752810000.95 258.177
10010.96258.751610030.98264.140410040.99267.875810061.01280.462110071.02285.7913
10081.05288.594810091.37289.044110141.87289.420710152.07289.621310162.27290.2363
10172.48290.333810193.01291.626710203.37291.938210224.09293.708210234.45294.2841
10265.52299.213310275.88302.166110286.24304.629110296.76306.548310300.84307.6624
#Mann= 3 , 0 , 0
 9875.09    0.04       0 9875.09    0.04       010300.84    0.04       0
#XS Ineff= 2 , 0
       0                               0
Bank Sta=9875.09,10300.84
Exp/Cntr=0.3,0.1

Type RM Length L Ch R = 1 ,15264.71,299.490800,299.490800,299.490800
XS GIS Cut Line= 6
826698.754281715 802757.98994309826762.359723864802825.964736169
826818.500247743802851.847984297826872.708046034802866.922664155
827019.347205488802883.570557141827135.978613201802905.165154025
#Sta/Elev= 30
9810.111 287.2699820.105286.59299858.075 287.3439880.574286.20159893.779284.3375
9906.561281.58499918.163281.06629929.575279.15229946.576273.92939976.452263.3954
9993.181258.616310003.57256.383810013.86258.090110044.34270.929410064.53281.6388
10074.58283.770910084.63283.838810104.74285.175410124.84 282.51510144.94278.5969
10154.99278.596710165.04 279.78410175.13281.955610185.25285.286610195.36287.1596
10205.48288.380710225.73289.1676 10256.4294.368510266.62295.328110288.07298.4707
#Mann= 3 , 0 , 0
9810.111    0.04       09810.111    0.04       010288.07    0.04       0
#XS Ineff= 2 , 0
       0                               0
Bank Sta=9810.111,10288.07
Exp/Cntr=0.3,0.1

Type RM Length L Ch R = 1 ,14965.22,444.238000,444.238000,444.238000
XS GIS Cut Line= 6
 826690.53040126802766.400729939826763.067023546802919.063215092
826777.316151559802971.000594154826781.309457272803121.646165937
826810.584616452803146.209757552827051.664383487803303.937145994
#Sta/Elev= 30
9565.431286.68989586.762286.5107 9598.23287.54179620.561285.82669653.431286.7933
9708.215281.10779751.106273.56529792.438267.35739812.449265.16239944.256259.5906
9971.404259.09269983.197256.04079994.479 251.3579997.203251.253610005.65251.5853
10028.78270.063810052.52271.266110076.86270.828710091.01271.5357 10101.2270.8366
10125.54 272.552 10137.7272.634810143.66271.641310161.21276.968410178.76280.9727
10198.55282.5071 10222.7 287.42810234.67287.966410250.33292.265610266.59294.6054
#Mann= 3 , 0 , 0
9565.431    0.04       09565.431    0.04       010266.59    0.04       0
#XS Ineff= 2 , 0
       0                               0
Bank Sta=9565.431,10266.59
Exp/Cntr=0.3,0.1

Type RM Length L Ch R = 1 ,14520.98,299.490800,299.490800,299.490800
XS GIS Cut Line= 6
826605.907186398802725.115843366826631.574859942802842.917443487
826561.496011869803013.075528134826662.767149806803211.519023165
826792.975483149803326.102356493826886.266367021803374.008486074
#Sta/Elev= 30
 9808.49286.69569841.458284.97489852.073282.76879883.117280.20819899.825282.4835
9923.326282.76459943.648277.07169953.909272.1894 9975.16257.76499985.951249.3092
9996.989 247.72610008.54249.568410020.09253.442110065.81257.080510162.34260.1655
10173.25258.422510184.16258.975210216.89258.002210243.81260.623710283.97 262.688
10304.05266.238610339.72266.944710435.94 276.75810450.95279.802310466.09 281.262
10481.22284.924610502.54287.183610526.68292.544910571.65306.821110618.04323.7088
#Mann= 3 , 0 , 0
 9808.49    0.04       0 9808.49    0.04       010618.04    0.04       0
#XS Ineff= 2 , 0
       0                               0
Bank Sta=9808.49,10618.04
Exp/Cntr=0.3,0.1

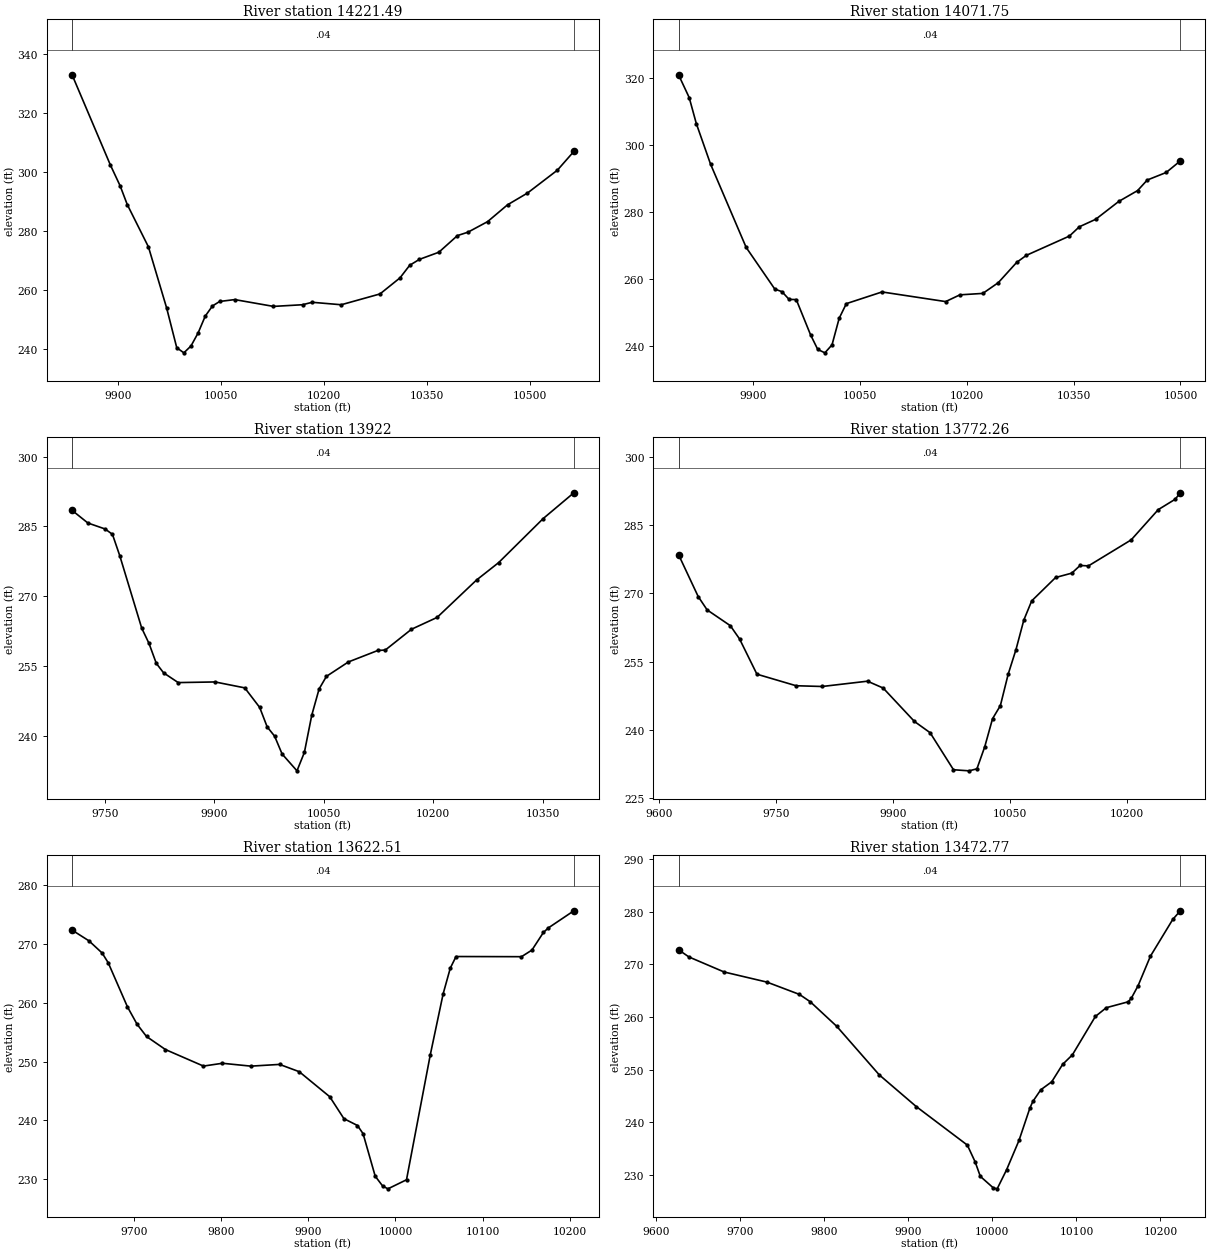
Type RM Length L Ch R = 1 ,14221.49,149.745400,149.745400,149.745400
XS GIS Cut Line= 6
826267.083262758803050.980570906826428.300675582803092.325519783
826456.819279631803100.547003138826492.485621905803112.380562873
826748.704649776803367.769023165826847.662983119803461.519023165
#Sta/Elev= 30
9832.556332.84979888.466302.31649902.696295.26859913.008288.97959943.943274.6381
9970.419254.03039985.222240.54769995.581238.817410005.97241.138410016.38245.5479
10026.79251.2471 10037.3254.669210047.84256.193910069.81256.823110126.29254.5203
10168.64255.085210182.76255.912210225.12255.0799 10281.6258.735210310.78264.1686
10324.94268.427410339.11270.427710367.44272.838310394.55278.465910409.93279.6226
10438.53283.188710467.61288.8767 10496.7292.853410540.32300.592310564.33306.9242
#Mann= 3 , 0 , 0
9832.556    0.04       09832.556    0.04       010564.33    0.04       0
#XS Ineff= 2 , 0
       0                               0
Bank Sta=9832.556,10564.33
Exp/Cntr=0.3,0.1

Type RM Length L Ch R = 1 ,14071.75,149.745300,149.745300,149.745300
XS GIS Cut Line= 6
826220.031302913803253.303998256826484.644082462803236.729235019
826539.967246841803245.223361573826571.943902737803265.846987819
826690.870064489803405.499005594826809.944483622803514.574522571
#Sta/Elev= 30
9794.915321.02659809.888314.2143 9819.89306.44219839.896294.31439889.946269.4067
9930.148256.96819940.198256.18949950.249 253.879  9960.3253.82949980.401243.2832
9990.451238.9329 10000.5237.905910010.55240.3025 10020.6248.250210030.64252.6115
10080.75256.107310170.14253.225710190.17 255.24210222.39 255.67210244.14258.8877
10269.98264.950110283.51267.048210344.04272.8147 10357.9275.5808 10380.9277.8218
10413.35283.165810439.84286.413810453.34289.561810479.95291.816710499.83295.2832
#Mann= 3 , 0 , 0
9794.915    0.04       09794.915    0.04       010499.83    0.04       0
#XS Ineff= 2 , 0
       0                               0
Bank Sta=9794.915,10499.83
Exp/Cntr=0.3,0.1

Type RM Length L Ch R = 1 ,   13922,149.745400,149.745400,149.745400
XS GIS Cut Line= 6
826160.074019772803409.136638618826299.837944715803416.208061891
826471.584439877 803384.41720332826567.731795529803381.176857989
826648.472655705 803414.46596222826797.920583501803529.174972717
#Sta/Elev= 30
9704.758288.45749726.427285.73719750.119 284.4479760.147283.29549770.174278.7036
9800.243263.1477 9810.25259.85459820.257 255.5669830.264253.5246 9850.31251.4286
9900.811251.56679941.564250.29399962.047246.08889972.288241.91039982.529 239.908
9992.771236.079310013.19232.456110023.35236.427110033.43244.401810043.51250.0545
10053.59252.768210083.69255.866310124.05258.332210134.35258.4278 10170.2262.8938
10205.35265.438310259.41273.477910289.69277.214710350.84286.692510392.88292.2342
#Mann= 3 , 0 , 0
9704.758    0.04       09704.758    0.04       010392.88    0.04       0
#XS Ineff= 2 , 0
       0                               0
Bank Sta=9704.758,10392.88
Exp/Cntr=0.3,0.1

Type RM Length L Ch R = 1 ,13772.26,149.745400,149.745400,149.745400
XS GIS Cut Line= 6
826111.495473035803472.067937794826231.192895164803512.223615103
826336.993049076803533.328359723826578.022916432803543.300127717
826645.381795676803566.175405831826729.300104457803612.499840124
#Sta/Elev= 30
9624.854278.54019650.055269.32319661.525266.38359691.227262.91639703.078259.9993
9725.366252.24199775.602249.70239809.021249.53719867.166250.70349887.255249.1921
9927.365241.84059947.365239.3801 9977.41 231.2239997.448 230.98410007.47231.4305
10017.48236.275810027.49  242.4510037.51245.320110047.53252.238710057.55257.6599
10067.58264.1424 10077.7268.365210108.36273.510110129.14274.471710139.76276.1565
10150.48276.065510205.26281.785510239.93288.432110261.68290.721310268.27292.1446
#Mann= 3 , 0 , 0
9624.854    0.04       09624.854    0.04       010268.27    0.04       0
#XS Ineff= 2 , 0
       0                               0
Bank Sta=9624.854,10268.27
Exp/Cntr=0.3,0.1

Type RM Length L Ch R = 1 ,13622.51,149.745400,149.745400,149.745400
XS GIS Cut Line= 6
826097.555108301803490.127046653 826308.00502298803583.456274785
826372.707326801803620.450745549 826399.37947761803642.791243136
826448.539457143803695.393685007826571.543374887803804.061583167
#Sta/Elev= 30
9628.902272.38549648.308270.55189663.392268.48299670.381266.82379692.454259.3117
9703.433256.36799714.322254.2686  9736.1252.04019779.657249.23029801.435249.7067
9834.103249.21879867.041249.51469889.594 248.2729924.575244.01239940.853240.2756
9956.427239.10929962.848 237.7159976.764230.48019985.321228.8041 9991.36228.3255
10012.67229.867810040.02251.186910054.74261.540810062.93265.911510069.51267.8837
10144.63267.855910156.62268.983210169.78271.9842 10175.4272.751710204.72275.6739
#Mann= 3 , 0 , 0
9628.902    0.04       09628.902    0.04       010204.72    0.04       0
#XS Ineff= 2 , 0
       0                               0
Bank Sta=9628.902,10204.72
Exp/Cntr=0.3,0.1

Type RM Length L Ch R = 1 ,13472.77,299.490800,299.490800,299.490800
XS GIS Cut Line= 6
826041.391416111803517.637156535826099.637391452803560.877794658
826173.422519549803620.793718131826220.694586485803665.289643386
826267.138009925803715.101495159826458.151285728803941.787897841
#Sta/Elev= 30
9626.598 272.802 9638.95271.4355 9680.91268.57079731.812266.65039770.457264.3095
9783.339262.91519814.916258.22689865.421249.00529909.413242.98069970.242235.6428
9979.568232.43429985.686 229.69710001.22227.492610005.71227.324210016.89 230.934
10031.68236.520410044.66242.692110048.24243.963410057.65246.171810070.64247.6858
10083.62250.997110095.26252.818610122.58260.115510135.57261.779710161.54262.8997
10165.21263.540910173.36265.948410188.05271.571710214.64278.567210223.66280.2185
#Mann= 3 , 0 , 0
9626.598    0.04       09626.598    0.04       010223.66    0.04       0
#XS Ineff= 2 , 0
       0                               0
Bank Sta=9626.598,10223.66
Exp/Cntr=0.3,0.1