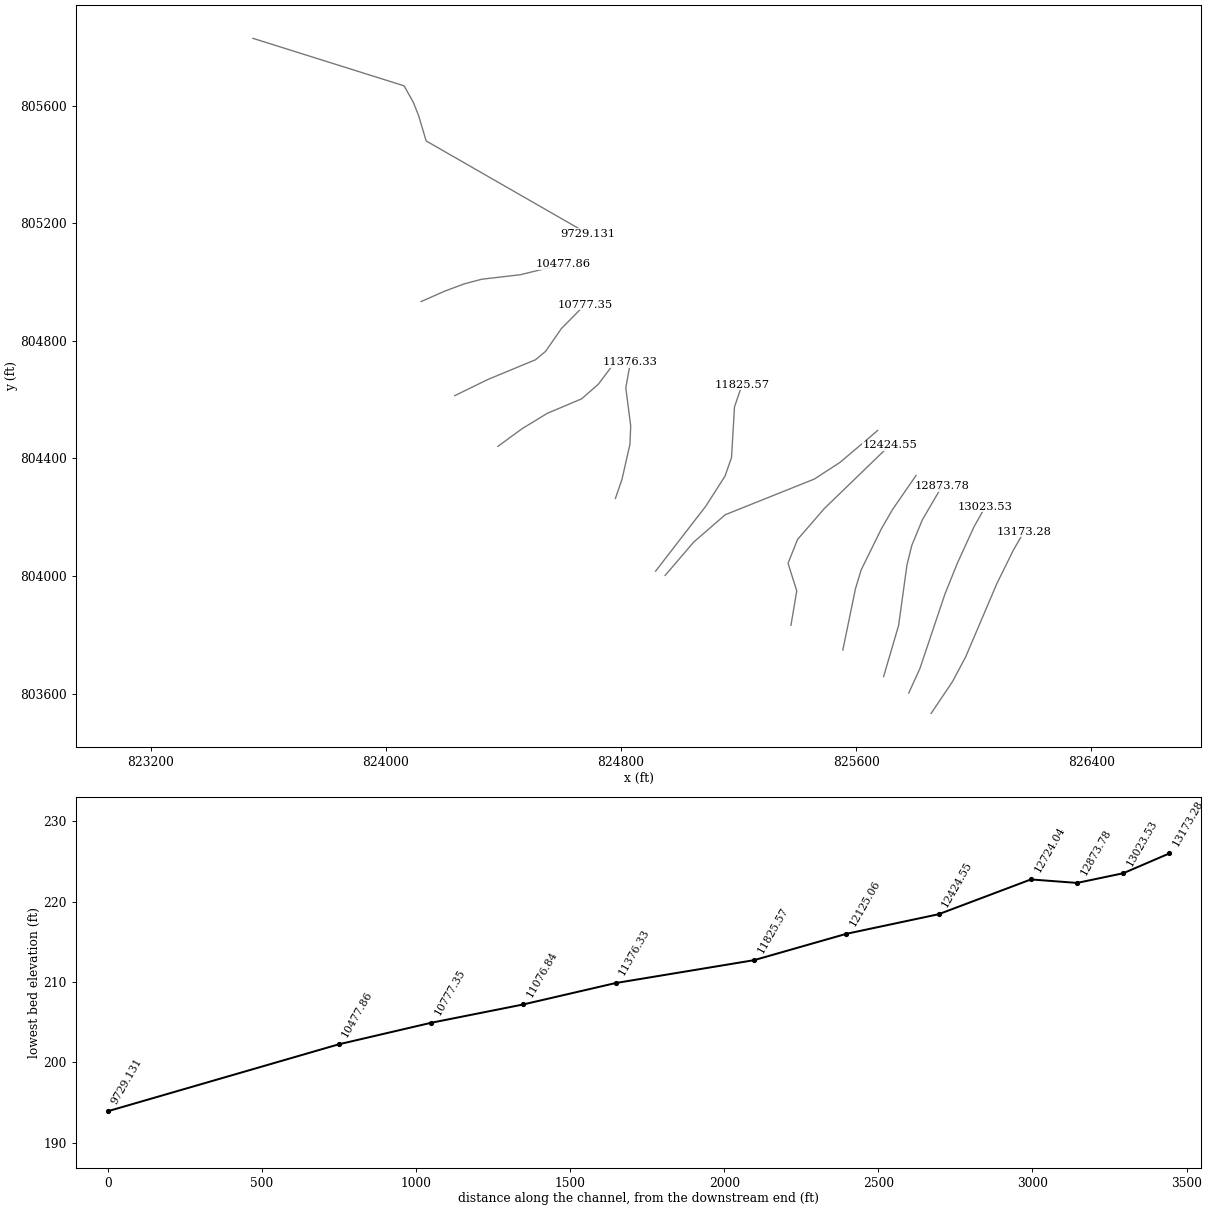
HEC-RAS study 18089_ras.prj: 18089

--- 18089_ras.g01 (geometry) --- (continued)

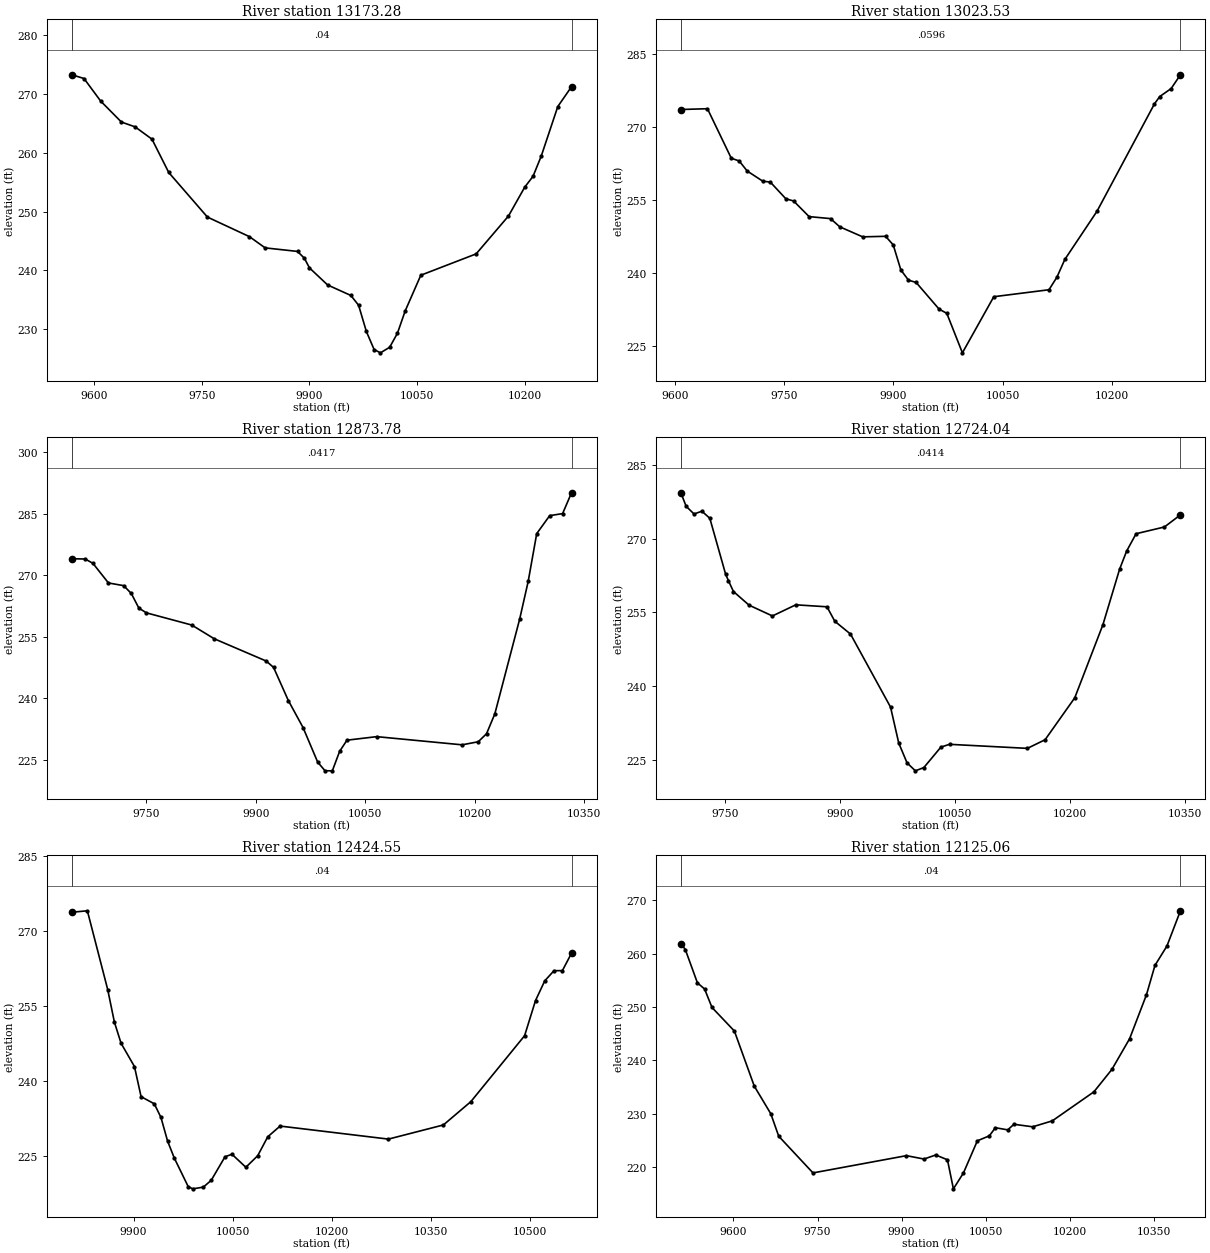
Type RM Length L Ch R = 1 ,13173.28,149.745300,149.745300,149.745300
XS GIS Cut Line= 6
825854.852681521803532.807057986825927.475310437803640.853585902
825972.084128709803724.776841355826078.560539974 803974.70993454
826134.834744827804088.764613211  826171.3196318804151.295362981
#Sta/Elev= 30
9568.857273.28289585.669272.64619608.928268.80539637.828 265.2419656.854264.4261
9680.436262.33099703.824256.66029757.771249.07429816.345245.74629838.276 243.836
9883.375243.23489892.959242.07549900.071240.42859925.371237.52629957.783235.7418
9968.588234.07559979.392229.61919990.196226.5447    9999225.980910011.86226.9237
10022.72229.310910033.59233.126510055.32239.184110132.51 242.81610177.56249.2543
10200.26254.171410211.77255.998410223.29259.455610246.32267.871110265.49271.2542
#Mann= 3 , 0 , 0
9568.857    0.04       09568.857    0.04       010265.49    0.04       0
#XS Ineff= 2 , 0
       0                               0
Bank Sta=9568.857,10265.49
Exp/Cntr=0.3,0.1

Type RM Length L Ch R = 1 ,13023.53,149.745400,149.745400,149.745400
XS GIS Cut Line= 6
825778.675779081803602.072272196825816.546471845803685.293688994
825901.432880365803937.735784698825943.807367572804043.352193596
826001.088786534804168.352135378826039.311579518804235.940927844
#Sta/Elev= 30
9607.676273.52589644.218273.68939676.972263.5119 9687.89 262.9479698.808260.8889
9720.105258.81099730.749258.59419752.037255.17459762.681254.72139783.969 251.513
9813.468251.10099826.113249.41669857.618247.35239889.123247.46499899.625245.7026
9910.127240.54459920.628 238.447 9931.13237.97939962.635232.50729973.296231.6313
9994.736223.5136 10037.9 235.04810113.78 236.48110124.67 239.05610135.56242.7089
10179.74252.598210258.79274.683310266.02276.185810281.68277.823810294.51280.6634
#Mann= 3 , 0 , 0
9607.676  0.0596       09607.676  0.0596       010294.51  0.0596       0
#XS Ineff= 2 , 0
       0                10051.63       0
Bank Sta=9607.676,10294.51
Exp/Cntr=0.3,0.1

Type RM Length L Ch R = 1 ,12873.78,149.745400,149.745400,149.745400
XS GIS Cut Line= 6
825693.067646681803657.903662889 825744.16225092803831.902629776
825772.613349143804037.782491831825788.884096148804103.811958886
825825.000090479804191.388859628825891.579831887804305.054284657
#Sta/Elev= 30
9648.247274.02669666.389 273.9559677.001272.89679698.223268.11799719.075267.4601
9729.493265.5611 9739.91261.98189750.328260.82499812.347257.85779843.096254.5141
9914.306249.08139924.414247.52539944.629239.45079964.764232.86669984.821 224.436
9994.849222.336510004.88222.310310014.93227.083410024.98229.787110065.61 230.647
10182.67228.652510204.76229.4022 10216.1231.362210227.43236.180510261.44259.2763
10273.14268.481810284.84280.148710302.61 284.52910320.28285.025510332.51290.1045
#Mann= 3 , 0 , 0
9648.247  0.0417       09648.247  0.0417       010332.51  0.0417       0
#XS Ineff= 2 , 0
       0                10037.82       0
Bank Sta=9648.247,10332.51
Exp/Cntr=0.3,0.1

Type RM Length L Ch R = 1 ,12724.04,299.490800,299.490800,299.490800
XS GIS Cut Line= 6
825554.432042694803748.318187222825597.234786677803955.963319497
825616.486742015804020.082754123825685.597855369804160.711530614
825723.167363717804225.616118777825803.390762783804341.892756568
#Sta/Elev= 30
9692.251 279.3579699.135276.60479709.437275.0404 9719.74275.60389730.043274.1595
9750.648262.78979754.323261.4713 9760.87259.25739781.224256.47759811.756254.2784
9842.287256.54659882.996256.14319893.173 253.1999913.673250.5924 9965.95235.7233
9976.667228.39659987.532224.35449998.396222.744310009.46223.415610031.68227.5725
10042.92228.142910144.59227.3205 10167.7229.074610206.44 237.61710243.16252.4861
10264.96263.799110274.18267.4993 10286.5271.021210323.48272.392910344.38274.8621
#Mann= 3 , 0 , 0
9692.251  0.0414       09692.251  0.0414       010344.38  0.0414       0
#XS Ineff= 2 , 0
       0                10050.33       0
Bank Sta=9692.251,10344.38
Exp/Cntr=0.3,0.1

Type RM Length L Ch R = 1 ,12424.55,299.490700,299.490700,299.490700
XS GIS Cut Line= 6
825377.991834088803832.438509557825397.746221815803949.327184694
825368.152875163804043.362407689825400.387499801804124.214503411
825490.984073473804228.927479845 825713.93959783804444.654823677
#Sta/Elev= 30
9806.723273.69059830.021273.98359860.798  258.249870.912251.73699881.025247.5027
9901.251242.85859911.285236.83899931.304235.40599941.321232.69069951.396227.9501
9961.544224.56319982.483218.88449989.425 218.41710005.41 218.75510017.38 220.121
10038.24224.826510048.72225.329110069.79222.728910087.69225.035610102.89228.8184
10121.57230.960710285.42 228.35610368.56231.182310410.12235.8432 10491.4249.0158
 10507.9256.033210521.89 259.98110535.88262.010910548.58262.023710562.39265.5068
#Mann= 3 , 0 , 0
9806.723    0.04       09806.723    0.04       010562.39    0.04       0
#XS Ineff= 2 , 0
       0                               0
Bank Sta=9806.723,10562.39
Exp/Cntr=0.3,0.1

Type RM Length L Ch R = 1 ,12125.06,299.490800,299.490800,299.490800
XS GIS Cut Line= 6
824950.051518298 804001.94510861825047.474901124804115.702988811
825154.482928254804208.384000279825457.660553755804329.837946778
825545.214466775804386.772991536825673.077870942804495.019277751
#Sta/Elev= 30
9506.192261.87099514.114260.74859535.714 254.5119548.519253.36239561.714249.9086
9601.663245.50119637.178235.18669666.635230.0278 9680.76225.82379741.904218.9587
9908.651222.18759939.995221.5523 9960.89222.31519981.786221.41159992.407215.9793
10010.28218.937110035.15224.965810056.54225.894510067.28227.411710089.34227.0115
10100.37 228.05810133.91227.583510168.87228.6977 10243.1234.127610275.24  238.33
10306.77244.058610336.88252.292210352.02257.782110373.37261.401410397.46267.9956
#Mann= 3 , 0 , 0
9506.192    0.04       09506.192    0.04       010397.46    0.04       0
#XS Ineff= 2 , 0
       09934.352                       0
Bank Sta=9506.192,10397.46
Exp/Cntr=0.3,0.1

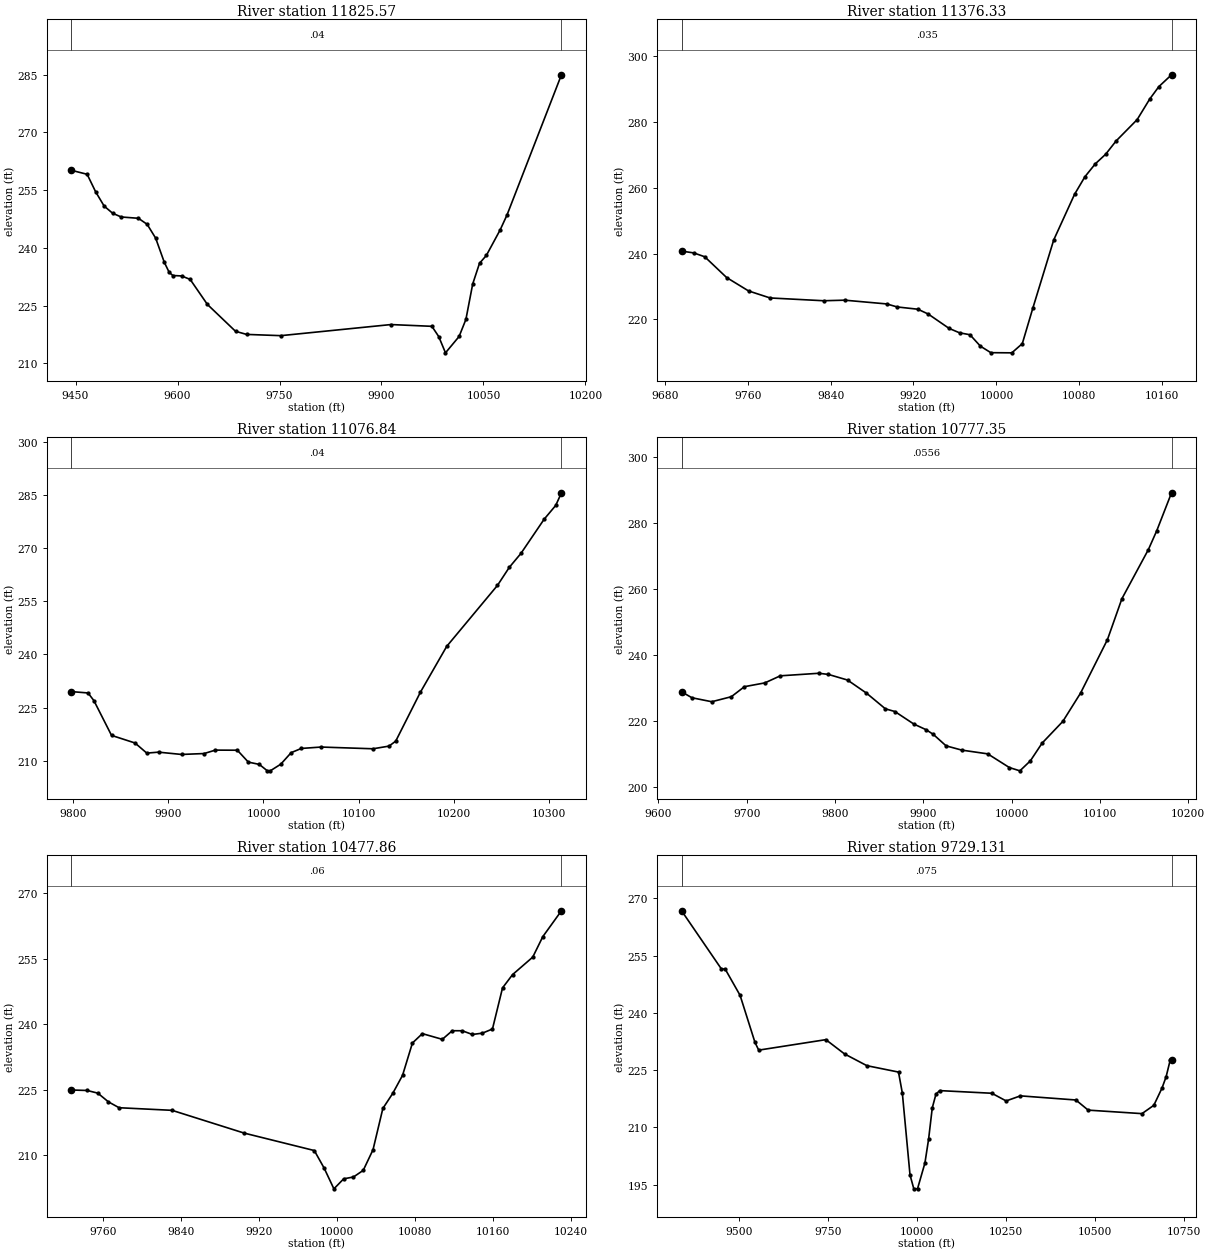
Type RM Length L Ch R = 1 ,11825.57,449.236200,449.236200,449.236200
XS GIS Cut Line= 6
 824917.61103139 804016.57513212825089.040854338 804238.40454279
825153.951809614 804340.13354852 825175.90284127804403.270316723
825185.971431411804575.158806675825211.791040262804650.641785416
#Sta/Elev= 30
9444.009260.1193 9467.05259.09359479.556254.53739492.062250.83359504.567248.9633
9517.147248.00069542.444247.6588 9555.29246.09689567.816242.50499580.502236.2423
9587.792233.58139593.189232.79359605.875232.68129618.561231.78469643.933225.2777
  9685.3218.29959701.551217.49039751.939217.16619913.919220.05019974.131219.5919
9984.133216.94599994.135212.701910014.14216.950710024.15221.384210034.16230.5947
10044.17 235.96510054.24238.011310074.49244.625310084.61248.512910164.68284.9454
#Mann= 3 , 0 , 0
9444.009    0.04       09444.009    0.04       010164.68    0.04       0
#XS Ineff= 2 , 0
       09948.713                       0
Bank Sta=9444.009,10164.68
Exp/Cntr=0.3,0.1

Type RM Length L Ch R = 1 ,11376.33,299.490700,299.490700,299.490700
XS GIS Cut Line= 6
824781.026770237804263.862908623824803.267841238804328.699938546
824830.435462665 804448.21215994824832.948889484804510.678967367
824816.292264303804639.539675541824831.828842644804726.586638779
#Sta/Elev= 30
9696.186240.7474 9707.96240.19429718.532239.02389739.676232.7158 9760.82228.6513
9781.582226.51999833.269225.67219853.614225.84519894.193224.70349904.233223.7896
9924.298223.09499934.299 221.6189954.334217.27879964.412215.93819974.491215.3518
9984.569211.87649994.647209.905810014.88209.8559   10025212.648710035.13223.3933
10055.33244.1412 10075.4257.969310085.42263.320210095.43267.235410105.43270.1535
10115.56274.199310135.84280.668110147.95286.911210156.77290.682910169.02  294.28
#Mann= 3 , 0 , 0
9696.186   0.035       09696.186   0.035       010169.02   0.035       0
#XS Ineff= 2 , 0
       0                               0
Bank Sta=9696.186,10169.02
Exp/Cntr=0.3,0.1

Type RM Length L Ch R = 1 ,11076.84,299.490800,299.490800,299.490800
XS GIS Cut Line= 6
824381.151538935804440.834439211824463.168997923804500.839251594
824549.582734887804553.474357805824666.195584735804602.648738806
824722.542511521804651.995583173824788.864438891804739.898948168
#Sta/Elev= 30
9798.161229.52749815.565229.14369821.746226.98299840.277217.18879864.988215.0425
9877.343212.19449889.699 212.4629913.853211.81679937.623212.06919949.447213.0366
9972.566213.00789984.126209.65689995.686209.009110004.12207.195610007.21207.2002
10018.22 209.06510029.14212.3163 10039.8213.506510060.61213.901110115.22213.4133
10132.05214.1649 10139.1215.564810165.05229.353310192.71242.273510246.05259.4477
10258.57264.562410270.77 268.47410295.17278.114610307.38282.013910313.36285.5664
#Mann= 3 , 0 , 0
9798.161    0.04       09798.161    0.04       010313.36    0.04       0
#XS Ineff= 2 , 0
       09960.655        10072.41       0
Bank Sta=9798.161,10313.36
Exp/Cntr=0.3,0.1

Type RM Length L Ch R = 1 ,10777.35,299.490700,299.490700,299.490700
XS GIS Cut Line= 6
 824234.61586609804613.402949601824346.172392638804667.956860247
824509.376689782804735.661487019824543.160237524804763.707810458
824597.274363623 804841.61287938824677.772161393 804923.20047609
#Sta/Elev= 30
9626.301228.8758 9638.08227.07389660.465225.87179682.649227.39459697.433230.4345
9720.549 231.5839738.107233.73039781.775234.50389792.625234.1466  9814.2232.4478
9835.638228.47969857.077223.71919867.796222.90359889.235219.10589903.183217.3796
9911.254215.98389925.789212.48969943.569211.19649972.934210.06039997.443205.9081
10009.33204.910810021.21 207.94310034.49213.312210057.99219.916210078.06228.5004
10108.44244.684810124.85257.116810154.87272.039910164.26277.704910181.05289.2445
#Mann= 3 , 0 , 0
9626.301  0.0556       09626.301  0.0556       010181.05  0.0556       0
#XS Ineff= 2 , 0
       0                               0
Bank Sta=9626.301,10181.05
Exp/Cntr=0.3,0.1

Type RM Length L Ch R = 1 ,10477.86,748.727000,748.727000,748.727000
XS GIS Cut Line= 6
824120.289331399804933.546913068824201.300351358804969.207322903
824267.353646564804993.735697537824326.236880698805009.364268386
824457.468120108805024.743943775824603.494545866805060.328381689
#Sta/Elev= 30
9727.841 224.8979743.913224.78979754.839224.17699765.765222.17059776.691220.8322
9830.967220.23569905.071215.00619976.854211.01479986.918206.99559996.951202.2334
10006.98204.526810017.01204.950810027.04206.472610037.07211.205510047.16220.6708
10057.26224.108410067.36228.264910077.47235.668610087.66237.821210108.11236.5147
10118.34238.487610128.57238.481910138.89237.629510149.22237.931110159.55238.8839
10169.88248.3129 10180.2251.364910200.86 255.36710211.19260.065410230.29265.9926
#Mann= 3 , 0 , 0
9727.841    0.06       09727.841    0.06       010230.29    0.06       0
#XS Ineff= 2 , 0
       0                               0
Bank Sta=9727.841,10230.29
Exp/Cntr=0.3,0.1

Type RM Length L Ch R = 1 ,9729.131,598.981500,598.981500,598.981500
XS GIS Cut Line= 6
823548.183816493805828.706523165824062.196026504805667.166872948
824093.227182537805611.950371116824111.502984256805566.437161282
824137.238448143  805479.7641204824688.156171799805163.590343565
#Sta/Elev= 30
9338.196266.73859450.163251.49049460.645251.48749502.574244.60289544.503232.2595
9554.985230.24519743.665232.98779796.076229.25439858.969226.17269947.823224.4989
9958.599218.99879980.151197.56379990.884193.918610001.35193.962510022.04200.6672
10032.38206.913610042.73215.128610053.07218.704510063.42219.645210210.08218.9507
10250.29216.941110290.46218.266410446.29217.186710480.87214.530110632.06213.6149
10665.34215.7917 10688.4220.315410699.93223.278210711.45227.664410715.14 227.615
#Mann= 3 , 0 , 0
9338.196   0.075       09338.196   0.075       010715.14   0.075       0
#XS Ineff= 2 , 0
       0                               0
Bank Sta=9338.196,10715.14
Exp/Cntr=0.3,0.1