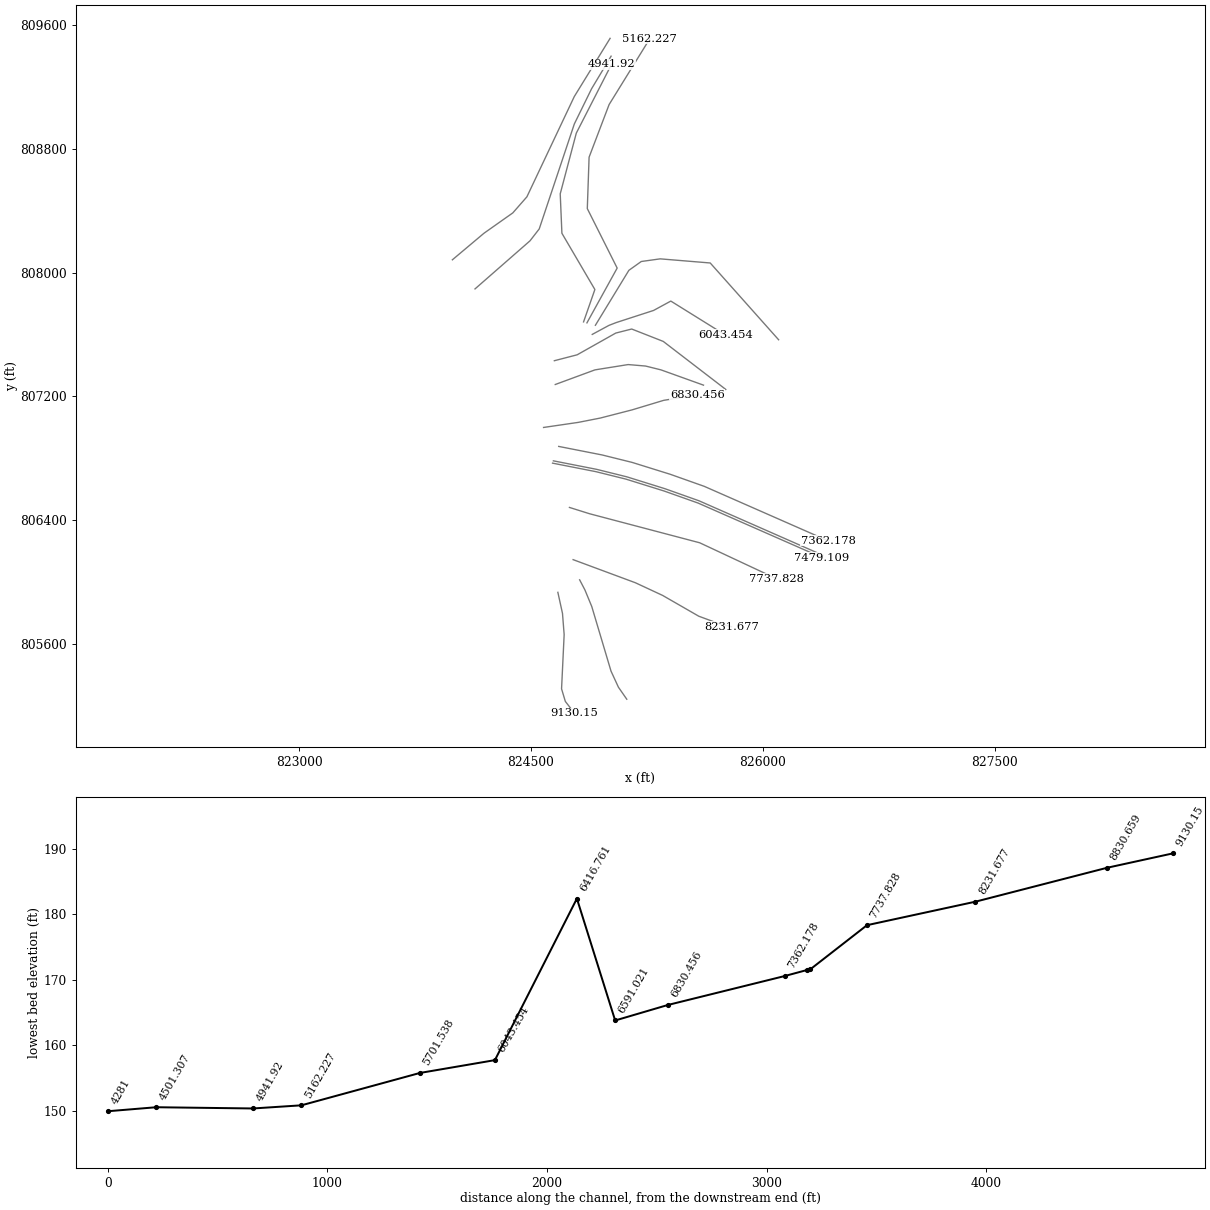
HEC-RAS study 18089_ras.prj: 18089

--- 18089_ras.g01 (geometry) --- (continued)

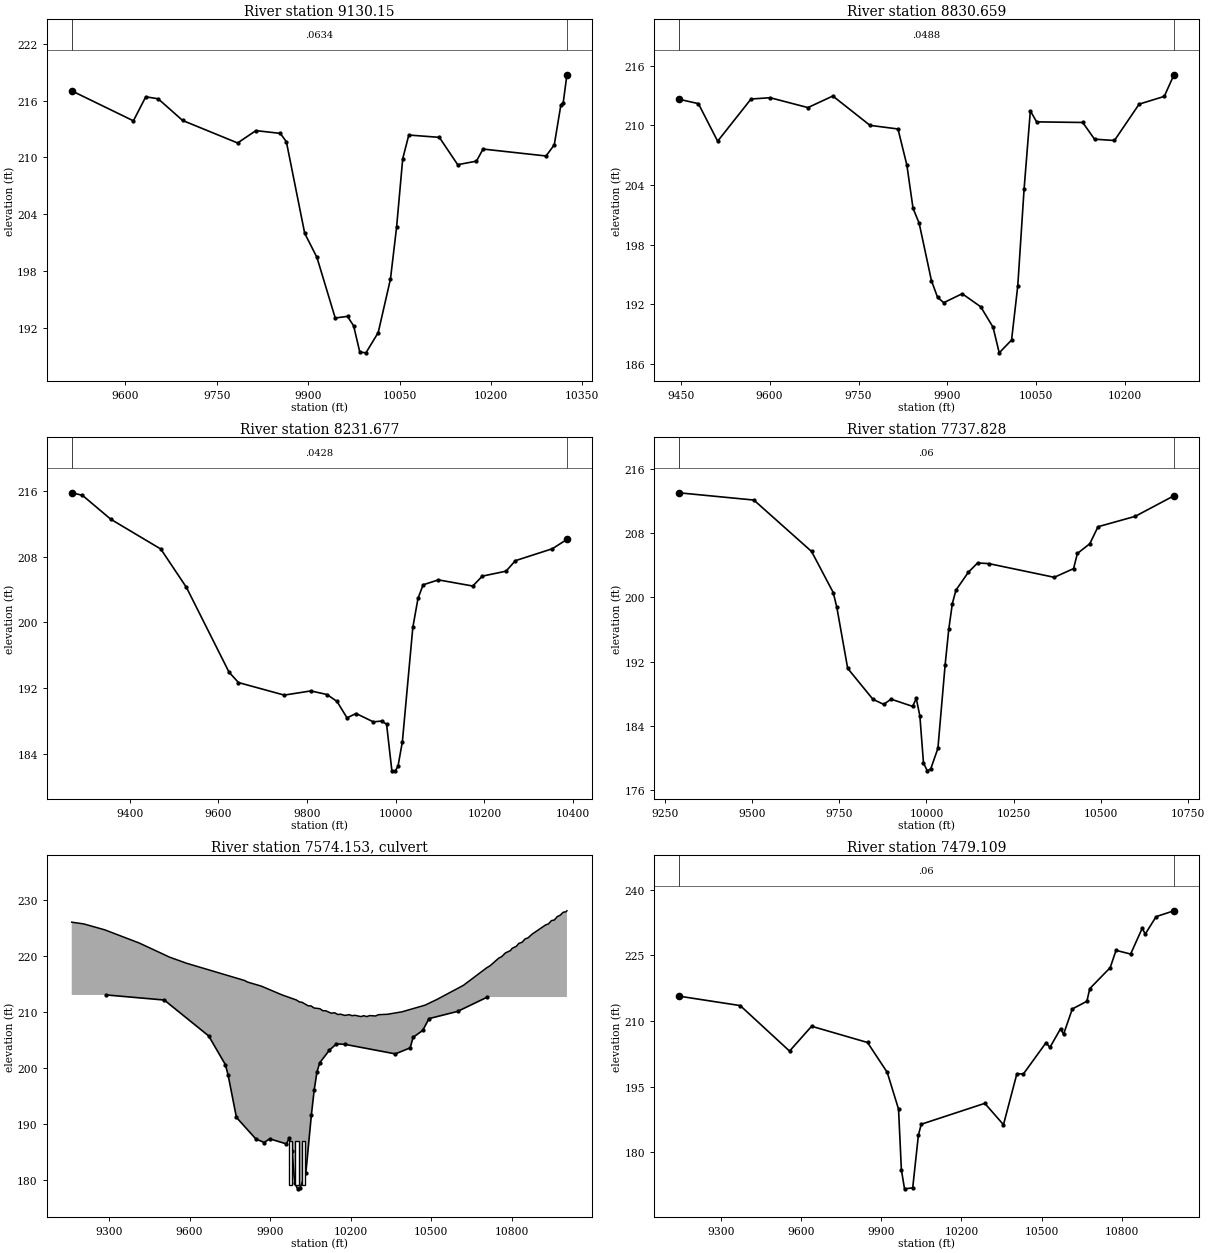
Type RM Length L Ch R = 1 , 9130.15,299.490800,299.490800,299.490800
XS GIS Cut Line= 6
824673.744200552805933.436018346824703.705149994 805797.04663434
824714.414120033805659.962111479824697.658445354805309.548418381
824722.094263308805228.062421142824782.310686931805150.805547348
#Sta/Elev= 30
9511.985217.04549613.195213.87439633.503216.41699653.791216.20639694.015213.9119
9784.259211.53189814.264212.83859854.272212.54679864.291211.66229894.349201.9814
9914.388199.43569944.475193.01519964.633193.19199974.712192.18039984.791189.4152
9994.871189.332110015.01191.473710035.13197.140810045.19 202.61710055.25 209.866
10065.25212.371210115.32212.126410145.51209.234610176.24209.610510187.12210.8887
10290.51210.155310304.01211.333910314.79215.535310318.65215.766210324.79218.7452
#Mann= 3 , 0 , 0
9511.985  0.0634       09511.985  0.0634       010324.79  0.0634       0
#XS Ineff= 2 , 0
       0                               0
Bank Sta=9511.985,10324.79
Exp/Cntr=0.3,0.1

Type RM Length L Ch R = 1 ,8830.659,598.981500,598.981500,598.981500
XS GIS Cut Line= 6
824814.654939131806014.329220111824848.959141629805948.616049032
824893.160954544805841.624729372825017.757311265805423.916855588
 825065.63331758805320.093848861825119.717327777805242.305653351
#Sta/Elev= 30
9446.829212.63469479.914212.18749512.401208.41029568.659212.65079600.891212.7819
9664.692211.79019706.671212.95299769.404210.00319816.589209.63979831.572206.0045
9841.933 201.6739852.294200.16129873.017194.38749883.378192.70859893.739192.1786
9924.882 193.076 9956.11191.76499976.928189.70839987.338187.133210008.16188.4198
10018.62193.869510029.23203.558710039.83211.459210050.43210.355510128.17210.2923
10148.11208.612110181.69208.481110223.35212.139210265.68212.912910282.08215.0883
#Mann= 3 , 0 , 0
9446.829  0.0488       09446.829  0.0488       010282.08  0.0488       0
#XS Ineff= 2 , 0
       0                               0
Bank Sta=9446.829,10282.08
Exp/Cntr=0.3,0.1

Type RM Length L Ch R = 1 ,8231.677,493.850000,493.850000,493.850000
XS GIS Cut Line= 6
824772.468034899806144.813539944825175.529770427805995.406498253
825352.117690266805913.282416014825585.709657048805779.023963613
825708.338074906805733.847595571825797.110159342805711.387883783
#Sta/Elev= 30
 9269.26215.7699 9293.29215.4629 9357.28212.55259470.122208.92589527.918204.2629
9623.903193.96029645.233192.68969748.411191.16449808.398191.67149845.025191.2338
 9867.53 190.3879890.029 188.3969910.399188.92639949.491187.90869967.978188.0094
9979.245187.62239991.135181.9762    9999181.953210005.02182.517410014.82185.4774
10038.44 199.40110050.11202.9262 10061.6204.576810096.09205.176510173.61204.4289
10195.18205.632710248.64206.236810269.73207.513910353.11 208.96410385.95 210.098
#Mann= 3 , 0 , 0
 9269.26  0.0428       0 9269.26  0.0428       010385.95  0.0428       0
#XS Ineff= 2 , 0
       09853.229                       0
Bank Sta=9269.26,10385.95
Exp/Cntr=0.3,0.1

Type RM Length L Ch R = 1 ,7737.828,258.718900,258.718900,258.718900
XS GIS Cut Line= 4
824748.758333137806482.396742587824879.682125503806441.415056887
825591.487681085806253.915056887826085.642921586806022.835268165
#Sta/Elev= 30
9290.472213.04829505.548212.14129671.005205.72499733.052200.59829743.393198.7403
9774.417191.14529846.804187.28449877.828186.6506 9898.51187.30569960.557186.4029
9970.898187.39179981.239185.2028 9991.58179.345310002.46178.361610012.26 178.595
10032.94181.169310053.63191.594710063.97195.995910074.31199.232810084.65 200.906
10120.23 203.138 10146.7204.294310178.66204.212710366.33 202.50410421.53203.5848
10432.57205.475510468.08206.692110491.69208.813310598.16210.107310709.26 212.676
#Mann= 3 , 0 , 0
9290.472    0.06       09290.472    0.06       010709.26    0.06       0
#XS Ineff= 2 , 0
       09953.673                       0
Bank Sta=9290.472,10709.26
Exp/Cntr=0.3,0.1

Type RM Length L Ch R = 2 ,7574.153,,,
Bridge Culvert--1,0,-1,-1, 0
Deck Dist Width WeirC Skew NumUp NumDn MinLoCord MaxHiCord MaxSubmerge Is_Ogee
29.359,200,2.6,0, 60, 60, , , 0.95, 0, 0,0,,
 9161.17 9206.02 9283.61 9412.65 9526.29 9588.28 9805.24 9815.57 9867.23 9943.22
 9997.7910008.7110019.6210041.4510052.3710063.2810085.1110096.0310106.9410127.91
10139.6910152.8610161.5210177.8110194.2710205.1810216.1010237.9310248.8410259.76
10270.6710292.5010303.4210336.1610390.7410477.1910521.7210619.9610707.2910718.21
10751.5410761.8710776.4610794.6310801.3910816.4610826.3110838.2910849.2110860.13
10876.1610925.6310936.5510947.4710958.3810969.3010980.2210991.1411002.0511005.27
  226.07  225.76  224.71  222.34  219.80  218.73  215.63  215.36  214.63  213.08
  212.15  211.81  211.72  211.11  211.09  210.72  210.59  210.24  210.22  209.78
  209.87  209.54  209.62  209.39  209.52  209.34  209.41  209.18  209.34  209.18
  209.36  209.29  209.52  209.59  210.03  211.23  212.26  214.78  217.94  218.24
  219.65  219.89  220.58  220.98  221.40  221.74  222.28  222.48  223.07  223.26
  223.95  225.57  225.77  226.35  226.46  227.07  227.32  227.84  227.94  228.11
                                                                                
                                                                                
                                                                                
                                                                                
                                                                                
                                                                                
 9161.17 9206.02 9283.61 9412.65 9526.29 9588.28 9805.24 9815.57 9867.23 9943.22
 9997.7910008.7110019.6210041.4510052.3710063.2810085.1110096.0310106.9410127.91
10139.6910152.8610161.5210177.8110194.2710205.1810216.1010237.9310248.8410259.76
10270.6710292.5010303.4210336.1610390.7410477.1910521.7210619.9610707.2910718.21
10751.5410761.8710776.4610794.6310801.3910816.4610826.3110838.2910849.2110860.13
10876.1610925.6310936.5510947.4710958.3810969.3010980.2210991.1411002.0511005.27
  226.07  225.76  224.71  222.34  219.80  218.73  215.63  215.36  214.63  213.08
  212.15  211.81  211.72  211.11  211.09  210.72  210.59  210.24  210.22  209.78
  209.87  209.54  209.62  209.39  209.52  209.34  209.41  209.18  209.34  209.18
  209.36  209.29  209.52  209.59  210.03  211.23  212.26  214.78  217.94  218.24
  219.65  219.89  220.58  220.98  221.40  221.74  222.28  222.48  223.07  223.26
  223.95  225.57  225.77  226.35  226.46  227.07  227.32  227.84  227.94  228.11
                                                                                
                                                                                
                                                                                
                                                                                
                                                                                
                                                                                
BR Coef=-1 , 0 , 0 ,, 0 ,,,0.8,-1,,0,
WSPro=,,,, 1 ,,,, 0 ,,,, 0 ,,,,-1 ,-1 ,-1 , 0 , 0 , 0 , 0 , 0
Multiple Barrel Culv=2,8,12,200,0.013,0.7,1,8,3,179,172.5,3,Culvert #1, 0, 29.359
 9976.00 9976.0010000.0010000.0010024.0010024.00
Culvert Bottom n=0.013
BC Design=,, 0 ,, 0 ,,,,,,

Type RM Length L Ch R = 1 ,7479.109,16.251100,16.251100,16.251100
XS GIS Cut Line= 6
824639.301338586806768.810204049824920.126609509806713.663247525
825114.658856307806665.381245464825361.098831748 806588.66324754
825581.584942882 806510.53824754826383.668276195806158.107691973
#Sta/Elev= 30
9141.307215.70129371.316213.53869556.242203.12369638.821208.80379848.288205.0895
9922.062198.26079964.499189.83679975.108175.95789986.889171.602410017.54171.8217
10038.76183.841410049.37186.383310287.59191.165510357.51186.278410407.74 197.947
10432.09197.883710516.96  205.0510531.52203.971910571.58208.2695 10582.5206.9624
10615.27212.761510669.88214.5177 10680.8 217.41910757.26222.218210779.11226.1772
10833.72225.328310877.41  231.2610888.34229.884910929.26233.893510996.11235.2309
#Mann= 3 , 0 , 0
9141.307    0.06       09141.307    0.06       010996.11    0.06       0
#XS Ineff= 2 , 0
       09915.344        10068.95       0
Bank Sta=9141.307,10996.11
Exp/Cntr=0.3,0.1

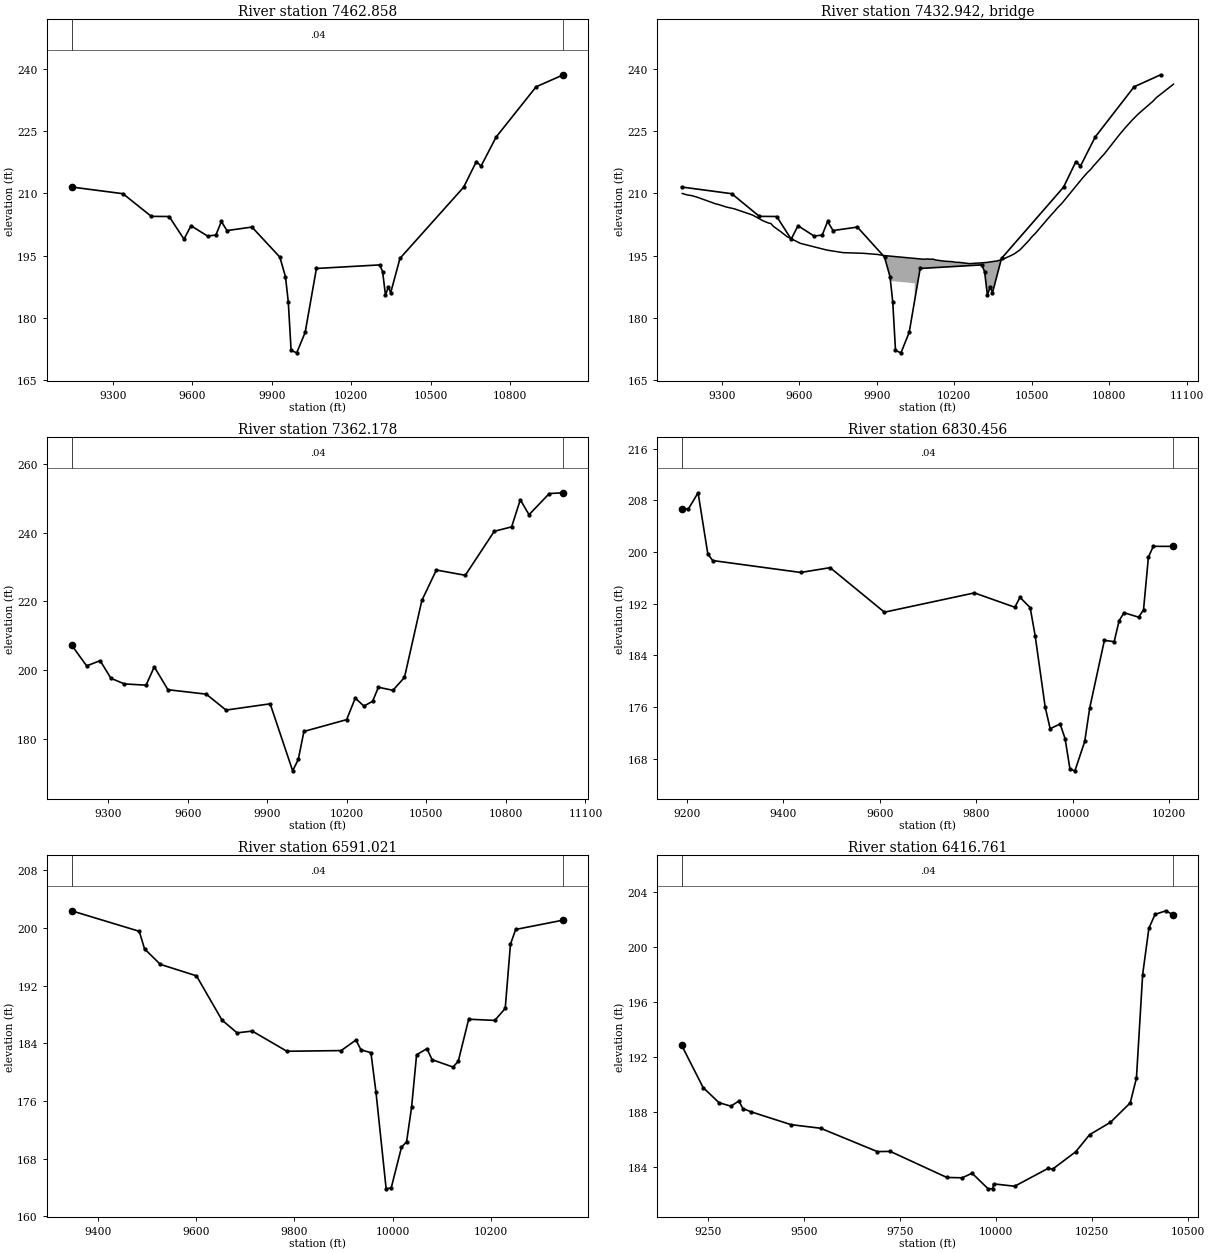
Type RM Length L Ch R = 1 ,7462.858,100.679500,100.679500,100.679500
XS GIS Cut Line= 6
824644.784612632806783.693376459824925.609883555806728.546419936
825120.142130353806680.264417874825366.582105793 806603.54641995
825587.068216928 806525.42141995826389.151550241806172.990864383
#Sta/Elev= 30
9145.049211.55379338.897209.93919445.805204.4642 9513.09204.42949569.036198.9559
9595.571202.20269657.767199.70789689.187199.94529710.134203.2317 9731.08201.0335
9825.341 201.8789930.596194.62139951.814189.88259962.424183.76849973.033172.0828
9994.251171.493310026.08176.442410068.52191.876510307.18192.738410318.11191.1139
10329.03185.401710339.95187.478810348.53185.994110383.64194.315710623.94211.5247
10671.69217.703410689.48216.619110746.27223.622310897.01235.762910999.85238.6693
#Mann= 3 , 0 , 0
9145.049    0.04       09145.049    0.04       010999.85    0.04       0
#XS Ineff= 2 , 0
       09914.715        10071.17       0
Bank Sta=9145.049,10999.85
Exp/Cntr=0.3,0.1

Type RM Length L Ch R = 3 ,7432.942,,,
BEGIN DESCRIPTION:
END DESCRIPTION:
Bridge Culvert--1,0,-1,-1, 0
Deck Dist Width WeirC Skew NumUp NumDn MinLoCord MaxHiCord MaxSubmerge Is_Ogee
33.339750,34.000000,2.6,0, 60, 60, , , 0.95, 0, 0,0,,
 9147.35 9165.00 9185.36 9205.72 9276.99 9287.17 9317.71 9348.25 9419.52 9460.25
 9480.61 9490.79 9499.95 9531.68 9552.41 9604.23 9707.88 9770.06 9848.71 9904.95
 9925.48 9954.17 9954.1710047.1710047.1710080.9810097.1410107.7010117.1610129.56
10162.1710194.7810205.6510219.1810260.0010325.2310368.7110390.4510423.0610433.93
10455.6710488.2810499.7510514.6810574.2110586.5710597.5210619.4010697.4610717.86
10728.8010739.8210783.9310841.0310861.1210888.4810912.2010971.4010982.4311049.62
  209.99  209.67  209.45  209.08  207.48  207.34  206.72  206.30  204.78  203.39
  202.87  202.72  202.06  200.63  199.59  197.95  196.31  195.70  195.54  195.25
  195.02  194.85  194.85  194.31  194.31  194.11  194.18  194.10  194.15  193.92
  193.64  193.51  193.37  193.35  193.04  193.32  193.72  194.15  195.08  195.44
  196.41  198.54  199.42  200.36  204.70  205.51  206.34  207.76  213.72  215.16
  215.79  216.65  219.72  224.26  225.75  227.64  229.15  232.35  233.11  236.40
 -790.01 -790.33 -790.55 -790.92 -792.52 -792.66 -793.28 -793.70 -795.22 -796.61
 -797.13 -797.28 -797.94 -799.37 -800.41 -802.05 -803.69 -804.30 -804.46 -804.75
 -804.98 -805.15  188.85  188.31 -805.69 -805.89 -805.82 -805.90 -805.85 -806.08
 -806.36 -806.49 -806.63 -806.65 -806.96 -806.68 -806.28 -805.85 -804.92 -804.56
 -803.59 -801.46 -800.58 -799.64 -795.30 -794.49 -793.66 -792.24 -786.28 -784.84
 -784.21 -783.35 -780.28 -775.74 -774.25 -772.36 -770.85 -767.65 -766.89 -763.60
 9147.35 9165.00 9185.36 9205.72 9276.99 9287.17 9317.71 9348.25 9419.52 9460.25
 9480.61 9490.79 9499.95 9531.68 9552.41 9604.23 9707.88 9770.06 9848.71 9904.95
 9925.48 9945.81 9945.8110038.8110038.8110080.9810097.1410107.7010117.1610129.56
10162.1710194.7810205.6510219.1810260.0010325.2310368.7110390.4510423.0610433.93
10455.6710488.2810499.7510514.6810574.2110586.5710597.5210619.4010697.4610717.86
10728.8010739.8210783.9310841.0310861.1210888.4810912.2010971.4010982.4311049.62
  209.99  209.67  209.45  209.08  207.48  207.34  206.72  206.30  204.78  203.39
  202.87  202.72  202.06  200.63  199.59  197.95  196.31  195.70  195.54  195.25
  195.02  194.90  194.90  194.36  194.36  194.11  194.18  194.10  194.15  193.92
  193.64  193.51  193.37  193.35  193.04  193.32  193.72  194.15  195.08  195.44
  196.41  198.54  199.42  200.36  204.70  205.51  206.34  207.76  213.72  215.16
  215.79  216.65  219.72  224.26  225.75  227.64  229.15  232.35  233.11  236.40
 -790.01 -790.33 -790.55 -790.92 -792.52 -792.66 -793.28 -793.70 -795.22 -796.61
 -797.13 -797.28 -797.94 -799.37 -800.41 -802.05 -803.69 -804.30 -804.46 -804.75
 -804.98 -805.10  188.90  188.36 -805.64 -805.89 -805.82 -805.90 -805.85 -806.08
 -806.36 -806.49 -806.63 -806.65 -806.96 -806.68 -806.28 -805.85 -804.92 -804.56
 -803.59 -801.46 -800.58 -799.64 -795.30 -794.49 -793.66 -792.24 -786.28 -784.84
 -784.21 -783.35 -780.28 -775.74 -774.25 -772.36 -770.85 -767.65 -766.89 -763.60
BR Coef=-1 , 0 , 0 ,, 0 ,,,0.8,0,1,0,
WSPro=,,,, 1 ,,,, 0 ,,,, 0 ,,,,-1 ,-1 ,-1 , 0 , 0 , 0 , 0 , 0
BC Design=,, 0 ,, 0 ,,,,,,

Type RM Length L Ch R = 1 ,7362.178,531.722000,531.722000,531.722000
XS GIS Cut Line= 6
824679.250906634806876.909035239824960.076177557806821.762078716
825154.608424356806773.480076654825401.048399796806696.762078731
 825621.53451093806618.637078731826423.617844244806266.206523163
#Sta/Elev= 30
9162.006207.2439 9218.82 201.1659269.775202.68369310.539197.54059361.494 195.904
9443.022195.54659473.892200.87859525.443194.22169670.047192.92589744.507188.2855
9910.988190.11029995.861170.579610017.08173.9001 10038.3 182.06110199.47185.4985
10231.88191.773310264.65189.457310297.42190.848210319.26194.943610373.88194.0434
10417.57 197.801 10483.1220.224710537.72229.099510646.93227.566410756.17240.3817
10821.71 241.67910854.48249.580210887.25245.219410963.71251.383411016.81251.6086
#Mann= 3 , 0 , 0
9162.006    0.04       09162.006    0.04       011016.81    0.04       0
#XS Ineff= 2 , 0
       09904.195        10064.64       0
Bank Sta=9162.006,11016.81
Exp/Cntr=0.3,0.1

Type RM Length L Ch R = 1 ,6830.456,239.435300,239.435300,239.435300
XS GIS Cut Line= 6
824581.236423523806999.559220963824805.728337635807032.354873381
824947.948637699 807060.26506866825154.362987602 807113.34331795
825358.178407937807174.767631272825576.577717466807210.905979489
#Sta/Elev= 30
  9189.3206.65529203.148206.6578 9223.27209.15379243.459199.68579253.553198.6754
 9435.85196.83269496.994 197.5759609.495190.68929795.972193.67199879.929191.4523
9890.424192.99159911.623191.39169921.908187.07099942.737176.01999953.049172.6711
9973.672173.40439983.984171.14349994.211166.373310004.39166.158810024.73170.7108
10034.91175.836510065.42186.330810085.76186.134710095.93189.360610106.06 190.609
10136.43189.920810146.56191.051610156.68 199.195 10166.8200.873410208.69200.8643
#Mann= 3 , 0 , 0
  9189.3    0.04       0  9189.3    0.04       010208.69    0.04       0
#XS Ineff= 2 , 0
       0 9888.81                       0
Bank Sta=9189.3,10208.69
Exp/Cntr=0.3,0.1

Type RM Length L Ch R = 1 ,6591.021,174.259700,174.259700,174.259700
XS GIS Cut Line= 6
824656.995054051807277.346738922824913.827387691807371.898072645
825128.591258377807406.189791009825241.365876794807396.672824532
   825341.347314807371.791170478825616.326177597807273.150967613
#Sta/Elev= 30
9346.574202.36529484.289199.51759494.967197.08819527.001194.93929600.655193.3388
9652.649187.19659683.367185.43089714.061185.67859784.741182.8767 9894.93 182.973
9925.117184.43259935.245183.08139955.573182.67739965.899177.17689986.551163.7939
9996.878 163.929 10017.7169.553210028.11170.328510038.29 175.10510048.47182.3868
10069.43 183.24310080.05181.707910122.55180.690910133.17181.470710154.42187.3243
10207.54187.156610228.79188.824410239.41 197.71810250.03199.775110347.06 201.073
#Mann= 3 , 0 , 0
9346.574    0.04       09346.574    0.04       010347.06    0.04       0
#XS Ineff= 2 , 0
       09942.548                       0
Bank Sta=9346.574,10347.06
Exp/Cntr=0.3,0.1

Type RM Length L Ch R = 1 ,6416.761,373.306500,373.306500,373.306500
XS GIS Cut Line= 6
824651.048399806807431.137078732824798.617844224 807469.33152315
825048.617844224 807609.95652315825151.631150365807636.034611732
825355.891299963807555.894265965825760.423399776807245.373189822
#Sta/Elev= 30
9181.844192.87119237.574189.79939278.892188.7006 9309.88188.44389330.539188.8194
 9341.22188.26869362.979188.02839466.495187.09869543.301186.83849690.999185.1391
 9724.57185.15379871.778 183.2589911.824183.23229937.507183.56489979.452182.4292
9991.494182.44429993.511182.7904 10048.4182.6189 10135.2183.914910147.22183.8657
10207.32185.127210243.53 186.37210297.59187.266910349.12188.682710365.29190.4895
10381.46198.023110397.63201.3879 10413.8202.402410442.09202.662410461.71202.3478
#Mann= 3 , 0 , 0
9181.844    0.04       09181.844    0.04       010461.71    0.04       0
#XS Ineff= 2 , 0
       09927.466        10097.56       0
Bank Sta=9181.844,10461.71
Exp/Cntr=0.3,0.1

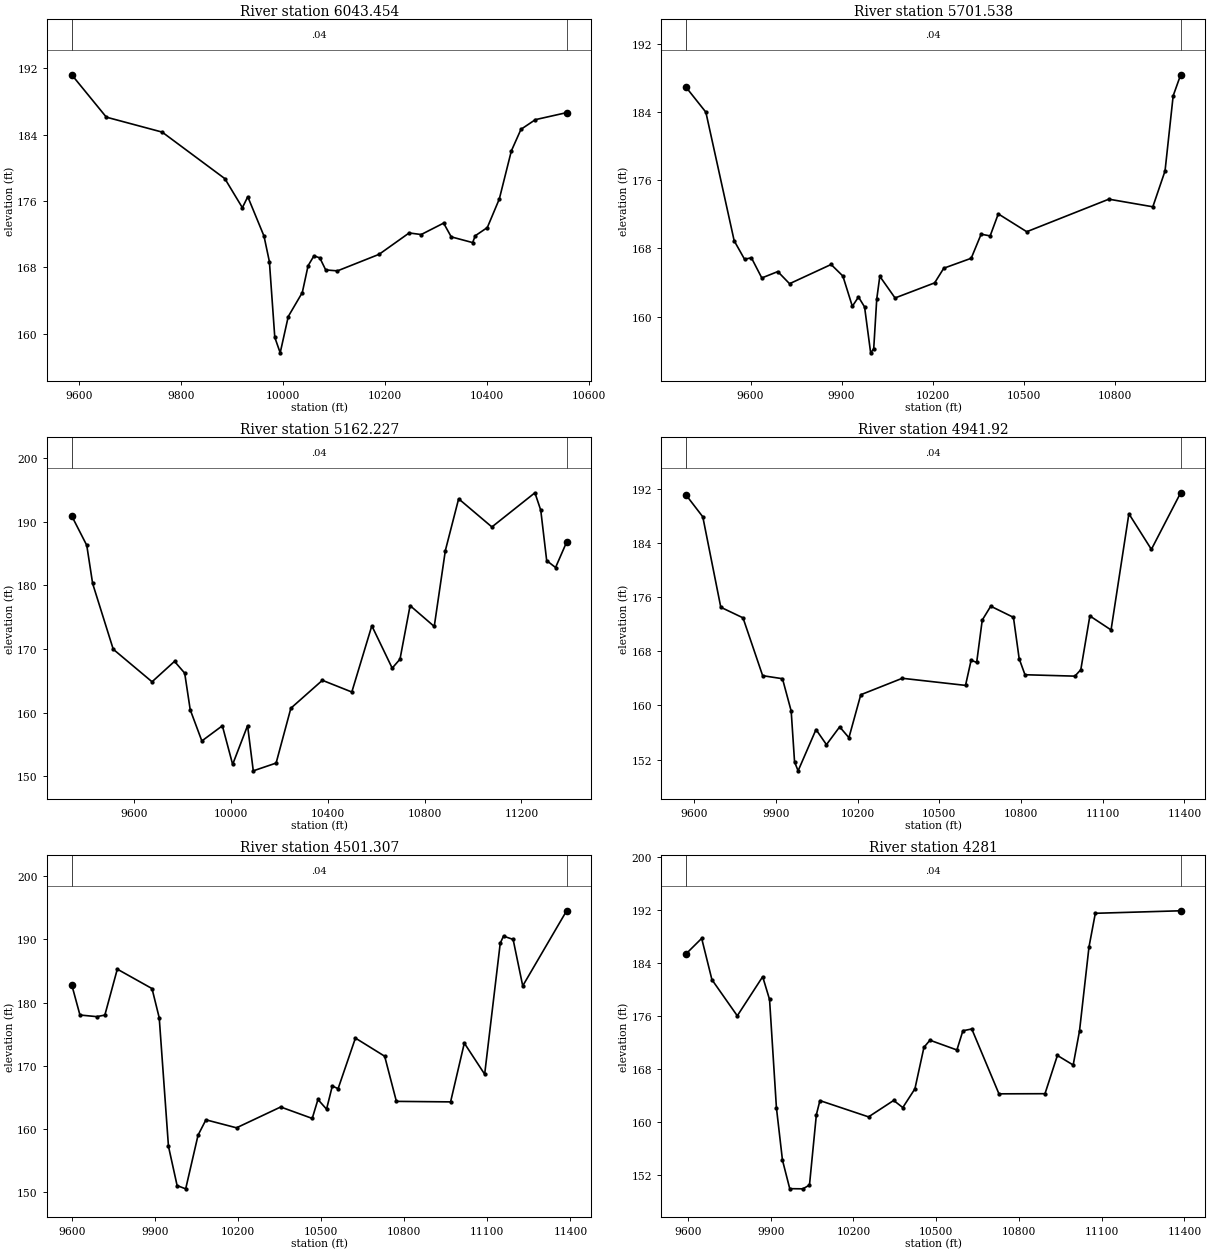
Type RM Length L Ch R = 1 ,6043.454,341.916500,341.916500,341.916500
XS GIS Cut Line= 6
824896.293740969807601.256599226825004.572044572807659.678903697
825051.445137999807677.813022245825293.274994548807756.207916378
825404.769213752807816.733862344825756.951177597807597.803745389
#Sta/Elev= 30
9586.236191.18749654.016186.08929763.372184.29039886.145178.68989920.461 175.195
9931.042176.51569962.786171.78329973.367 168.7089983.948159.59849994.529157.7321
10010.33162.101310037.83164.985110049.17168.216110060.66169.400410072.15169.1568
10083.65167.708710106.64167.593410188.22169.5848 10247.1172.157610270.64171.9653
10314.61173.340510329.52171.685910371.43170.997210376.62171.820310400.17172.8034
10423.72176.250810447.27182.027710466.14 184.62810494.36185.788710555.53186.6323
#Mann= 3 , 0 , 0
9586.236    0.04       09586.236    0.04       010555.53    0.04       0
#XS Ineff= 2 , 0
       0                               0
Bank Sta=9586.236,10555.53
Exp/Cntr=0.3,0.1

Type RM Length L Ch R = 1 ,5701.538,539.310700,539.310700,539.310700
XS GIS Cut Line= 6
824916.625483394807660.317435801825133.311804384808015.581201106
825213.612493724808072.662991643825335.808181256808089.741716221
825659.728955358808063.081523165826102.437288702807566.553745389
#Sta/Elev= 30
9386.675186.93229452.859183.96879546.153168.89859580.223166.74149602.937166.9038
9637.157 164.5449689.839165.29029728.567163.86899865.432166.12139904.205 164.769
 9935.37161.22429955.672162.31269975.698161.14399995.716155.769310005.75156.2264
10015.82162.0858 10025.9164.735910076.07162.197910206.51163.967110236.61165.6851
10326.91166.848210359.65169.670210389.35169.470310416.14172.049510509.93169.9603
10780.39173.774110925.25172.881610965.45177.078910992.24185.882911016.96188.3491
#Mann= 3 , 0 , 0
9386.675    0.04       09386.675    0.04       011016.96    0.04       0
#XS Ineff= 2 , 0
       09858.648        10124.36       0
Bank Sta=9386.675,11016.96
Exp/Cntr=0.3,0.1

Type RM Length L Ch R = 1 ,5162.227,220.306900,220.306900,220.306900
XS GIS Cut Line= 6
824861.944774607807675.940495436825057.577442303808030.075977142
824864.273345206808414.696885469824875.835484919808747.075133507
825005.434963426 809087.53007134825268.183313758809512.421639982
#Sta/Elev= 30
9341.573190.93379403.741186.30439427.963 180.3029513.127169.9558 9673.51164.8356
9766.256168.04979808.373 166.1979831.173160.44069879.229155.52629963.996157.9157
10006.51151.835710068.18157.938210091.75150.824910186.08 152.04710247.04160.6777
10377.26165.070610498.91163.226710581.59 173.64910665.73166.985710697.96168.3926
10739.71 176.82110839.53173.5409 10885.4185.485410940.32193.628111077.73189.1969
 11255.5194.575611279.66191.822911304.11183.904111340.78182.815211386.52186.8132
#Mann= 3 , 0 , 0
9341.573    0.04       09341.573    0.04       011386.52    0.04       0
#XS Ineff= 2 , 0
       0                               0
Bank Sta=9341.573,11386.52
Exp/Cntr=0.3,0.1

Type RM Length L Ch R = 1 , 4941.92,440.613600,440.613600,440.613600
XS GIS Cut Line= 6
824840.079459993807682.187728187824913.254488856 807891.42663294
824699.898177071 808255.17401885824689.016535721808510.138606105
824793.121128814808902.873393948825020.568925357 809346.87924494
#Sta/Elev= 30
9569.258191.11529631.779187.84339697.863 174.4929779.446172.92939851.589164.3911
9924.394 163.9449956.338159.17269968.751 151.6639981.769150.344110047.51 156.441
10085.89154.209310134.37156.836310168.38155.236710211.86161.576410364.27164.0063
10596.54 162.95710617.01166.663410637.48166.351810657.95172.5993 10689.1174.6472
 10772.5173.001410793.56166.889510814.82164.530110998.03164.321811019.81165.2697
11053.08173.2098 11130.9 171.14211196.39 188.293   11279 183.03411386.54  191.39
#Mann= 3 , 0 , 0
9569.258    0.04       09569.258    0.04       011386.54    0.04       0
#XS Ineff= 2 , 0
       0                               0
Bank Sta=9569.258,11386.54
Exp/Cntr=0.3,0.1

Type RM Length L Ch R = 1 ,4501.307,220.306800,220.306800,220.306800
XS GIS Cut Line= 6
824137.550033758807895.392351504824493.518687509808206.382124954
824553.095554525808283.217408854824780.409460095808962.254701957
824891.827006894809189.361154857825018.299375182 809400.24570994
#Sta/Elev= 30
 9600.02182.82829629.701178.03669690.353177.77779719.606178.02539764.558185.2922
 9889.86182.21989915.903177.59759949.222157.27059980.448151.051610011.41150.5328
10056.09159.0282 10084.5161.453710194.88160.188810354.36163.4839 10468.2161.6722
10488.89164.671410519.94 163.13710540.76 166.808 10561.6166.377610624.14174.3851
10729.72 171.51610772.06164.371610967.68164.290511017.23173.587611090.68168.6683
11146.97189.404811158.73190.517411193.42189.996611228.11182.642911386.59194.5281
#Mann= 3 , 0 , 0
 9600.02    0.04       0 9600.02    0.04       011386.59    0.04       0
#XS Ineff= 2 , 0
       0                               0
Bank Sta=9600.02,11386.59
Exp/Cntr=0.3,0.1

Type RM Length L Ch R = 1 ,    4281,0.000000,0.000000,0.000000
XS GIS Cut Line= 6
823991.052348504808083.585531822824195.851024712808255.600183172
824382.226591891808386.956823121824473.284776849808490.736877321
824780.007833114809139.155909643825011.818978542809515.621764246
#Sta/Elev= 30
9592.172185.35269649.843187.73499687.014181.49839778.965176.04319871.035181.9503
9895.953 178.5089920.872162.16179942.761154.25889969.189149.946610016.94149.9209
10040.74150.495910065.75161.128910078.57163.2428 10254.9160.786310346.01163.2678
10379.03162.191610423.05165.021910455.78171.289410477.51  172.3610575.28170.8871
10597.01173.786910629.22174.055410727.75164.263710894.67164.284610939.59170.0604
10996.85168.6143 11019.8173.752511054.22186.443511077.16191.5207 11386.6191.9008
#Mann= 3 , 0 , 0
9592.172    0.04       09592.172    0.04       0 11386.6    0.04       0
#XS Ineff= 2 , 0
       09860.077                       0
Bank Sta=9592.172,11386.6
Exp/Cntr=0.3,0.1